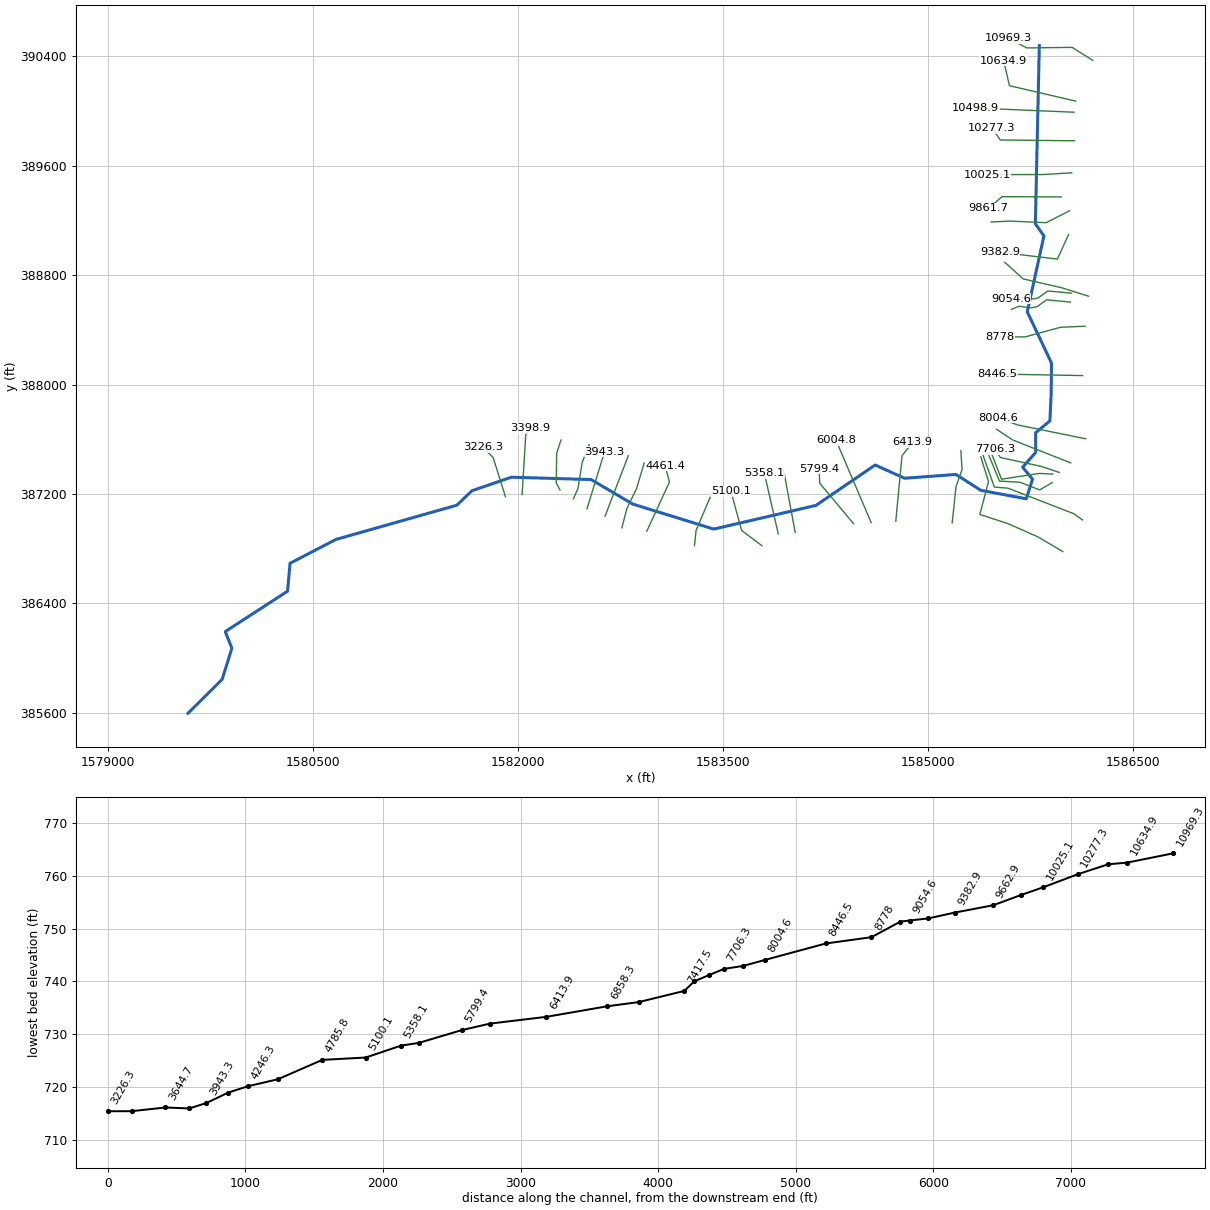
--- TENMLRUN.prj (project) ---

Proj Title=TENMLRUN
Current Plan=p01
Default Exp/Contr=0,0
English Units
Geom File=g01
Geom File=g02
Flow File=f01
Plan File=p01
BEGIN DESCRIPTION:
END DESCRIPTION:
DSS Export Rating Curves= 0
DSS Export Rating Curve Sorted= 0
DSS Export Volume Flow Curves= 0
DXF OffsetX= 0
DXF OffsetY= 0
DXF ScaleX= 0
DXF ScaleY= 0

--- TENMLRUN.p01 (plan) ---

Plan Title=Floodplain
Program Version=4.00
Geom File=g01
Flow File=f01
K Sum by GR=0
Std Step Tol=0.01
Critical Tol=0.01
Num of Std Step Trials=20
Max Error Tol=0.3
Flow Tol Ratio=0.001
Split Flow NTrial=30
Split Flow Tol=0.02
Split Flow Ratio=0.02
Log Output Level=0
Friction Slope Method=1
Unsteady Friction Slope Method=2
Unsteady Bridges Friction Slope Method=1
Global Log Level=0
CheckData=False
Run HTab=0
Run UNet=0
Run PostProcess=0
UNET Theta=0
UNET Theta Warmup=0
UNET ZTol=0
UNET ZSATol=0
UNET MxIter=0
UNET MaxInSteps=0
UNET DtIC=0
UNET DtMin=0
UNET MaxCRTS=0
UNET WFStab=0
UNET SFStab=0
UNET WFX=0
UNET SFX=0
UNET DSS MLevel=0
UNET DZMax Abort=0
UNET Convert EG Bridges=0
UNET Use Existing IB Tables=0
UNET Froude Limit=0
UNET Froude Power=0
Write IC File=0
Echo Input=False
Echo Output=False
Write Detailed=0

--- TENMLRUN.f01 (steady flow) ---

Flow Title=NFF Regression Equation
Program Version=4.10
Number of Profiles= 1
Profile Names=P100yr
River Rch & RM=TENMLRUN,Main            ,10969.3
1187.744
River Rch & RM=TENMLRUN,Main            ,7489.7
785.3044
River Rch & RM=TENMLRUN,Main            ,7084.7
 1674.38
River Rch & RM=TENMLRUN,Main            ,558.5
1815.198
Boundary for River Rch & Prof#=TENMLRUN,Main            , 1
Up Type= 0
Dn Type= 3
Dn Slope=0.007
DSS Import GetInterval= 0
DSS Import GetPeak= 0
DSS Import FillOption= 0

--- TENMLRUN.g01 (geometry) ---

Geom Title=USGS 10m DEM
Program Version=4.10

River Reach=TENMLRUN        ,Main
Reach XY= 30
     1585815.641       390478.03     1585786.558      389175.416
     1585849.448      389086.353     1585727.414       388531.49
     1585904.704      388157.265     1585902.126      387928.207
     1585892.937      387733.762     1585788.524      387647.463
      1585788.79      387503.102     1585693.789      387395.329
     1585766.112      387307.489     1585720.417      387164.295
     1585386.997      387226.461      1585205.89      387342.474
     1584829.705      387314.556     1584614.476      387411.355
     1584181.411      387116.099      1583433.68      386942.795
     1582839.687      387126.182     1582535.835      387305.113
     1581952.697      387322.156     1581664.566      387223.519
     1581553.592      387117.541     1580669.078      386867.207
     1580333.114      386692.876     1580315.102      386488.867
     1579859.316      386193.529     1579907.455      386071.649
     1579836.276      385844.298     1579586.084        385595.3

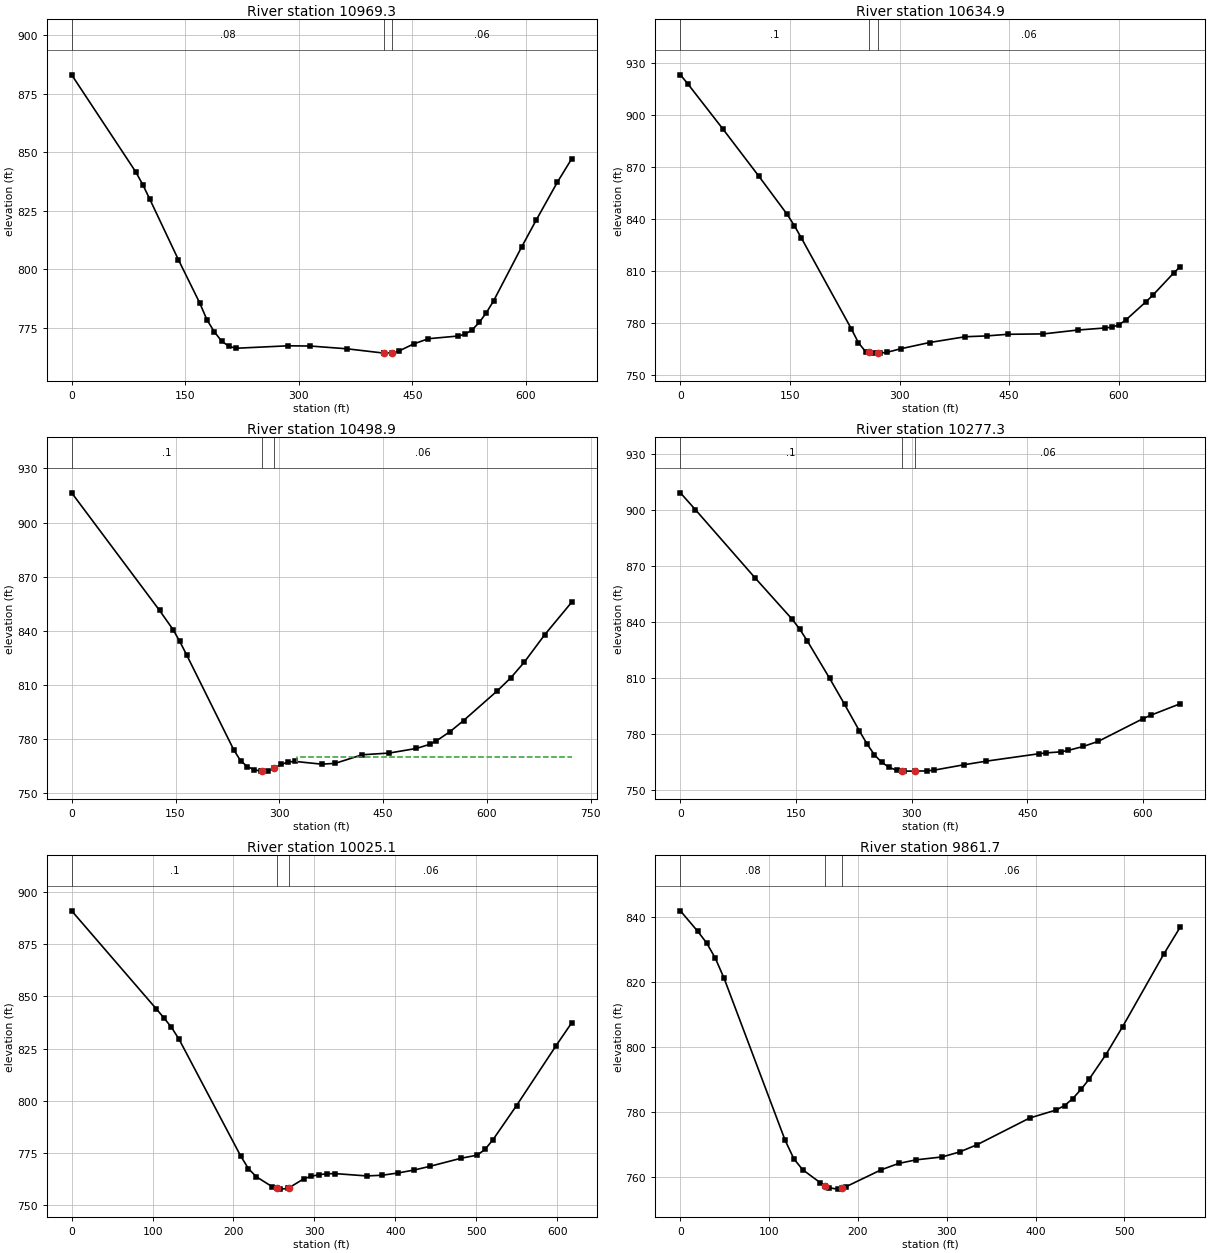
Type RM Length L Ch R = 1 ,10969.3 ,339.4,334.4,328.5
XS GIS Cut Line= 4
     1586206.974      390369.866     1586055.933      390465.352
     1585724.306      390461.095     1585591.523      390531.324
#Sta/Elev= 30
       0  883.12    84.6  841.69      94  836.18   103.4  829.88   141.1  804.08
   169.3  785.59   178.7   778.5   188.4  773.38   198.2  769.35     208   767.1
   217.7  766.34     286  767.38   315.3  767.28     364  766.09   412.2764.2682
   412.8  764.25   423.5764.4058   432.3  765.14   451.8  768.18   471.3  770.41
   510.4  771.55   519.7  772.32   529.1   774.2   538.5  777.38   547.9  781.56
   557.3  786.51   594.8  809.79   613.6  821.01   641.8  837.34   660.6  847.26
#Mann= 3 , 0 , 0
       0     .08       0   412.2    .045       0   423.5     .06       0
Bank Sta=412.2,423.5
XS Rating Curve= 0 ,0
Exp/Cntr=0.3,0.1

Type RM Length L Ch R = 1 ,10634.9 ,131.5,136,139.9
XS GIS Cut Line= 3
     1586081.281      390072.416     1585597.163      390185.057
     1585554.891      390367.609
#Sta/Elev= 30
       0  923.42     9.8   918.4    58.5  891.93   107.2  864.92   146.2  842.71
   155.9  836.27   165.7  828.98   233.9  776.62   243.6  768.58   253.4   763.4
   258.1762.9957   263.1  762.56     270762.5169   272.9   762.5   282.6  762.96
   302.1  765.07   341.1  768.64   389.8  771.98   419.1  772.45   448.3  773.39
     497  773.62   543.9  775.85   581.4  777.05   590.7  777.54   600.1  778.86
   609.5  781.59   637.6  792.33     647  796.14   675.1   808.8   684.4  812.59
#Mann= 3 , 0 , 0
       0      .1       0   258.1    .045       0     270     .06       0
Bank Sta=258.1,270
XS Rating Curve= 0 ,0
Exp/Cntr=0.3,0.1

Type RM Length L Ch R = 1 ,10498.9 ,220.9,221.6,222.1
XS GIS Cut Line= 2
     1586070.316      389991.064     1585348.706        390021.6
#Sta/Elev= 30
       0  916.49   126.9  851.32   146.4  840.69   156.2  834.08   165.9  826.76
   234.2  773.95     244  767.95   253.8  764.68   263.5  763.01   273.1  762.19
  275.47762.2307     283  762.36   292.1763.7997   302.6  765.91   312.3  767.19
   322.1  767.59   361.1  766.05   380.6   766.5   419.7  771.26   458.7  772.21
   497.8  774.76   517.3  777.05     527  779.01   546.6   784.1   566.1  790.23
   614.9  806.74   634.4  813.96   653.9  822.65   683.2  837.75   722.3  855.85
#Mann= 3 , 0 , 0
       0      .1       0  275.47    .045       0   292.1     .06       0
#XS Ineff= 2 , 0
       0                     325       0     770
Permanent Ineff=
       F       F
Bank Sta=275.47,292.1
XS Rating Curve= 0 ,0
Exp/Cntr=0.3,0.1

Type RM Length L Ch R = 1 ,10277.3 ,251.2,252.1,251.8
XS GIS Cut Line= 3
     1586072.469      389782.322     1585530.361      389788.046
     1585468.563      389874.813
#Sta/Elev= 30
       0  909.27    19.4  900.29    96.8  863.78   145.2  841.52   154.9  836.27
   164.6  830.03   193.6  809.99     213  796.05   232.3   781.8     242  774.94
   251.7  769.06   261.4  764.92   271.1  762.29   280.8  760.72   287.2760.4417
   290.4   760.3   304.8760.3048   319.5  760.41   329.2  760.83   367.9  763.71
   396.9  765.64   464.7  769.58   474.4  770.06   493.7  770.62   503.4  771.42
   522.8  773.53   542.1  776.23   600.2  788.39   609.9  790.16   648.7  796.42
#Mann= 3 , 0 , 0
       0      .1       0   287.2    .045       0   304.8     .06       0
Bank Sta=287.2,304.8
XS Rating Curve= 0 ,0
Exp/Cntr=0.3,0.1

Type RM Length L Ch R = 1 ,10025.1 ,163.6,163.4,163.3
XS GIS Cut Line= 3
     1586052.482      389548.019     1585844.149      389535.433
      1585434.86      389534.808
#Sta/Elev= 30
       0  890.92   104.4  844.11   113.8  839.83   123.3  835.23   132.8  829.43
   208.7   773.8   218.5  767.59   228.2  763.75   247.7  759.01   253.8  758.26
   257.4  757.82   267.2  758.14   268.8   758.5   286.7  762.71   296.4  763.99
   306.2  764.76   315.9  765.16   325.6  765.25   364.6  764.13   384.1  764.47
   403.6  765.57   423.1  766.94   442.6  768.71   481.6  772.62   501.1  774.06
   510.8  776.79   520.6   781.4   549.8  797.77   598.5  826.32     618  837.37
#Mann= 3 , 0 , 0
       0      .1       0   253.8    .045       0   268.8     .06       0
Bank Sta=253.8,268.8
XS Rating Curve= 0 ,0
Exp/Cntr=0.3,0.1

Type RM Length L Ch R = 1 ,9861.7  ,197.5,198.8,196.9
XS GIS Cut Line= 3
     1585975.224      389371.634     1585542.496       389373.61
     1585444.409      389287.603
#Sta/Elev= 30
       0  841.77    19.7  835.43    29.5  831.94    39.3  827.26    49.2  821.08
     118  771.32   127.8  765.65   137.7  762.31   157.4  758.34     163757.4412
   167.2  756.77     177  756.34   182.5756.7794   186.9  757.13   226.2  762.28
   245.9  764.23   265.5  765.33     295  766.23   314.7  767.77   334.4     770
   393.4  778.17   422.9   780.6   432.7  781.98     442  784.14   451.4  787.01
   460.7  790.21   479.3  797.64     498  806.16   544.6  828.55   563.2  836.87
#Mann= 3 , 0 , 0
       0     .08       0     163    .045       0   182.5     .06       0
Bank Sta=163,182.5
XS Rating Curve= 0 ,0
Exp/Cntr=0.3,0.1

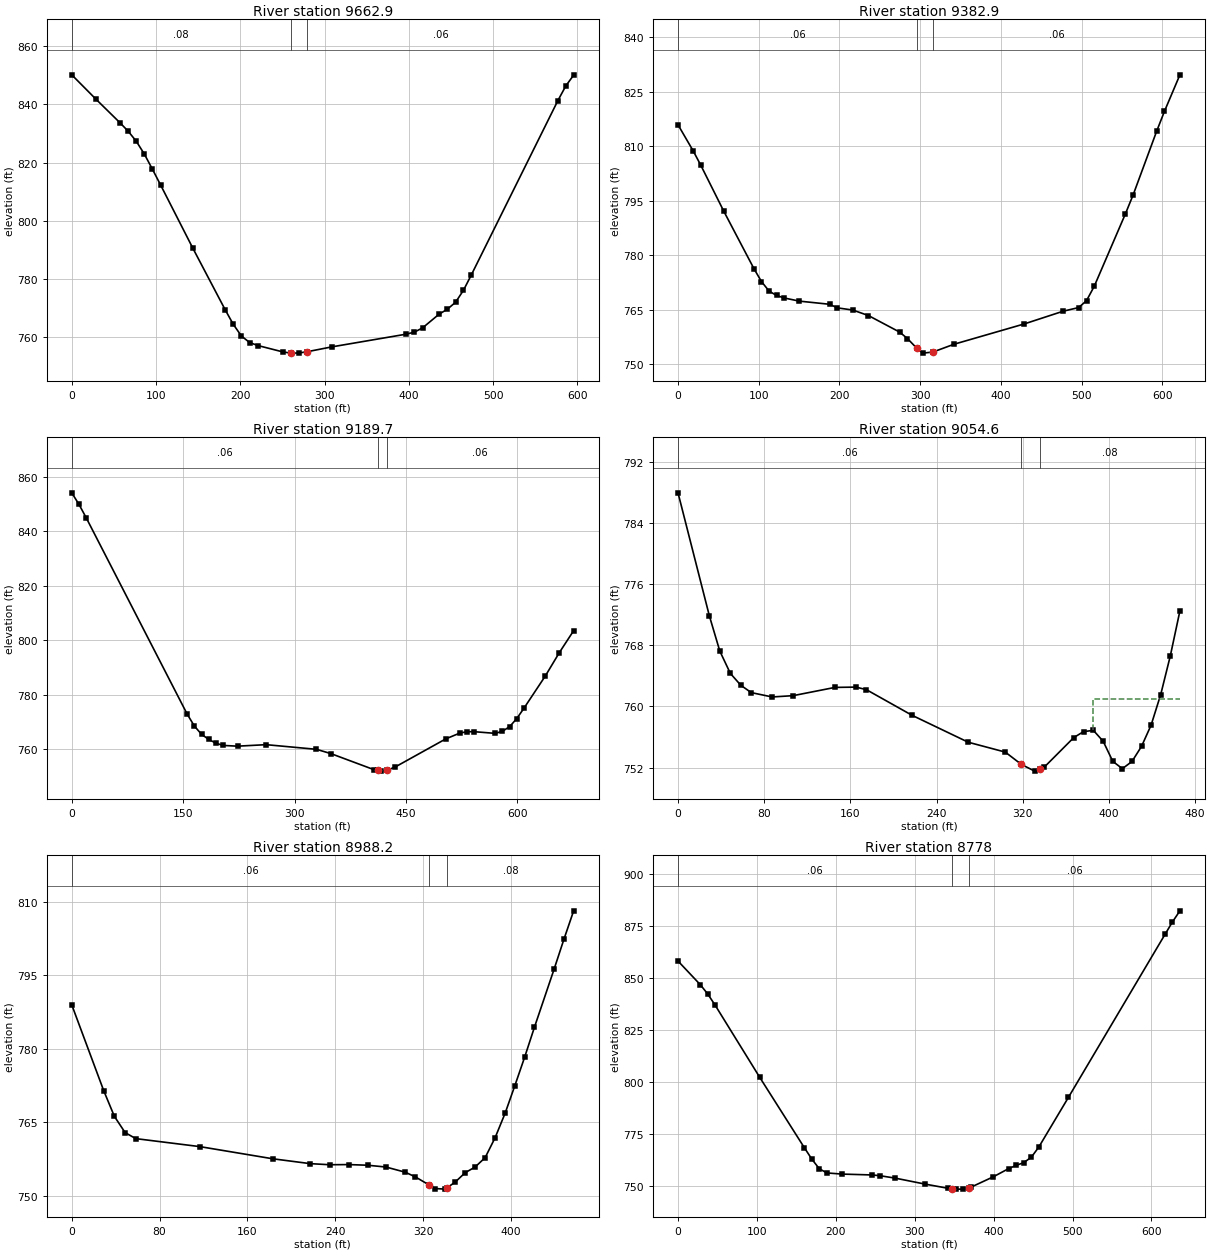
Type RM Length L Ch R = 1 ,9662.9  ,282.6,280,276.4
XS GIS Cut Line= 4
     1586036.534      389270.433     1585866.015      389183.193
     1585602.419       389195.08     1585462.369      389188.401
#Sta/Elev= 30
       0  850.18    28.7   841.8    57.5  833.61      67  830.76    76.6  827.31
    86.2  822.88    95.8  817.66   105.4   812.3   143.6  790.58     182  769.39
   191.5  764.42   201.3  760.33   211.1  758.07   220.9  757.04   250.2  754.87
     260  754.43   269.7  754.48   279.6 754.926   308.8  756.59   396.8  760.95
   406.5  761.64   416.3  763.11   435.9  767.83   445.6  769.51   455.4  771.91
   464.8  776.03   474.1  781.29   576.9  841.32   586.3  846.36   595.6  850.08
#Mann= 3 , 0 , 0
       0     .08       0     260    .045       0   279.6     .06       0
Bank Sta=260,279.6
XS Rating Curve= 0 ,0
Exp/Cntr=0.3,0.1

Type RM Length L Ch R = 1 ,9382.9  ,195,193.2,190.5
XS GIS Cut Line= 3
     1586029.724      389096.573     1585947.743      388917.102
     1585526.173      388967.244
#Sta/Elev= 30
       0  815.87    18.8  808.69    28.2  804.75    56.4  792.22      94  776.31
   103.4  772.73   112.8  770.12   122.1   768.9   131.5  768.22   150.3  767.35
   187.9  766.48   197.3   765.5   216.6  764.89   235.9  763.38   274.5  758.84
   284.2  757.06     296754.3439   303.4  753.04   315.7753.3322     342  755.49
   428.9  761.07   477.1  764.57   496.4  765.58   506.1  767.48   515.7  771.44
   554.3  791.37     564  796.65   592.9  814.04   602.6  819.54   621.8  829.62
#Mann= 3 , 0 , 0
       0     .06       0     296    .045       0   315.7     .06       0
Bank Sta=296,315.7
XS Rating Curve= 0 ,0
Exp/Cntr=0.3,0.1

Type RM Length L Ch R = 1 ,9189.7  ,130.1,135.1,136
XS GIS Cut Line= 4
     1586175.005      388646.054     1585980.573      388707.297
     1585697.913      388772.178     1585562.737      388893.884
#Sta/Elev= 30
       0  854.17     9.7  849.93    19.4  845.03   155.3  772.93     165  768.53
   174.7  765.47   184.4  763.58   194.1   762.2   203.8  761.37   223.2   761.1
   261.8  761.65   329.5  759.94   348.8  758.38   406.9  752.47   411.9752.1902
   416.5  751.93   424.4752.2174   435.9  753.51   503.4  763.74   522.6  765.92
   532.2   766.4   541.7  766.42   570.4   765.8     580  766.58   589.6  768.27
   599.2  771.23   608.7  774.96   637.5  786.81   656.6   795.5   675.8  803.53
#Mann= 3 , 0 , 0
       0     .06       0   411.9    .045       0   424.4     .06       0
Bank Sta=411.9,424.4
XS Rating Curve= 0 ,0
Exp/Cntr=0.3,0.1

Type RM Length L Ch R = 1 ,9054.6  ,69.3,66.5,66.6
XS GIS Cut Line= 6
     1586051.835      388667.553      1585877.79      388684.046
     1585808.779      388634.567     1585776.227      388625.886
     1585677.269      388637.171     1585606.817      388626.295
#Sta/Elev= 30
       0  787.94    29.1  771.85    38.8  767.24    48.6  764.32    58.3  762.77
      68  761.81    87.4  761.24   106.8  761.41   145.7  762.49   165.1  762.53
   174.8   762.2   217.3  758.84   269.4  755.32   303.8  754.03   318.8752.4112
   331.1  751.54   336.3  751.85   340.2  752.09   367.4  755.93   376.5  756.71
   385.6  756.87   394.7  755.44   403.6  752.82   412.5  751.86   421.4   752.8
   430.3  754.78   439.2  757.57   448.1  761.56     457  766.61   465.9  772.49
#Mann= 3 , 0 , 0
       0     .06       0   318.8    .045       0   336.3     .08       0
#XS Ineff= 2 , 0
       0                  385.62       0     761
Permanent Ineff=
       F       F
Bank Sta=318.8,336.3
XS Rating Curve= 0 ,0
Exp/Cntr=0.3,0.1

Type RM Length L Ch R = 1 ,8988.2  ,200.9,210.2,219.3
XS GIS Cut Line= 6
     1586043.374      388602.774     1585869.329      388619.267
     1585800.319      388569.788     1585749.538      388559.806
     1585668.808      388572.392     1585610.723      388549.472
#Sta/Elev= 30
       0  788.95    29.1  771.43    38.8  766.19    48.6  762.87    58.3  761.64
   116.6  760.01   183.2  757.52   217.3  756.53   234.8  756.31   252.2  756.34
   269.4  756.21   286.2  755.84   303.8  754.78     313  753.82   325.5 752.175
   331.1  751.45   340.2  751.33     342  751.62   349.3  752.79   358.3  754.68
   367.4  755.85   376.5  757.76   385.6  761.84   394.7  766.83   403.6  772.48
   412.5  778.28   421.4  784.38   439.3  796.23   448.2   802.3   457.1  808.14
#Mann= 3 , 0 , 0
       0     .06       0   325.5    .045       0     342     .08       0
Bank Sta=325.5,342
XS Rating Curve= 0 ,0
Exp/Cntr=0.3,0.1

Type RM Length L Ch R = 1 ,8778    ,336.2,331.5,324.1
XS GIS Cut Line= 4
     1586150.582      388426.437     1585971.718      388418.558
     1585712.332      388348.229     1585524.063      388348.095
#Sta/Elev= 30
       0  858.25    28.3  846.84    37.7  842.36    47.1  836.96   103.6  802.21
   160.2  768.29   169.6  762.83     179  758.23   188.6  756.18   207.8  755.63
   246.2   755.2   255.8  754.85     275   753.7   313.4  750.78   342.2  748.79
   347.6748.5586   351.8  748.38   361.4  748.38   369.3749.1108     371  749.27
   399.8  754.35     419  758.25   428.6  759.82   438.2  761.15   447.8  763.75
   457.2   768.6   494.9  792.63   617.2  871.07   626.6  877.05   636.1  882.44
#Mann= 3 , 0 , 0
       0     .06       0   347.6    .045       0   369.3     .06       0
Bank Sta=347.6,369.3
XS Rating Curve= 0 ,0
Exp/Cntr=0.3,0.1

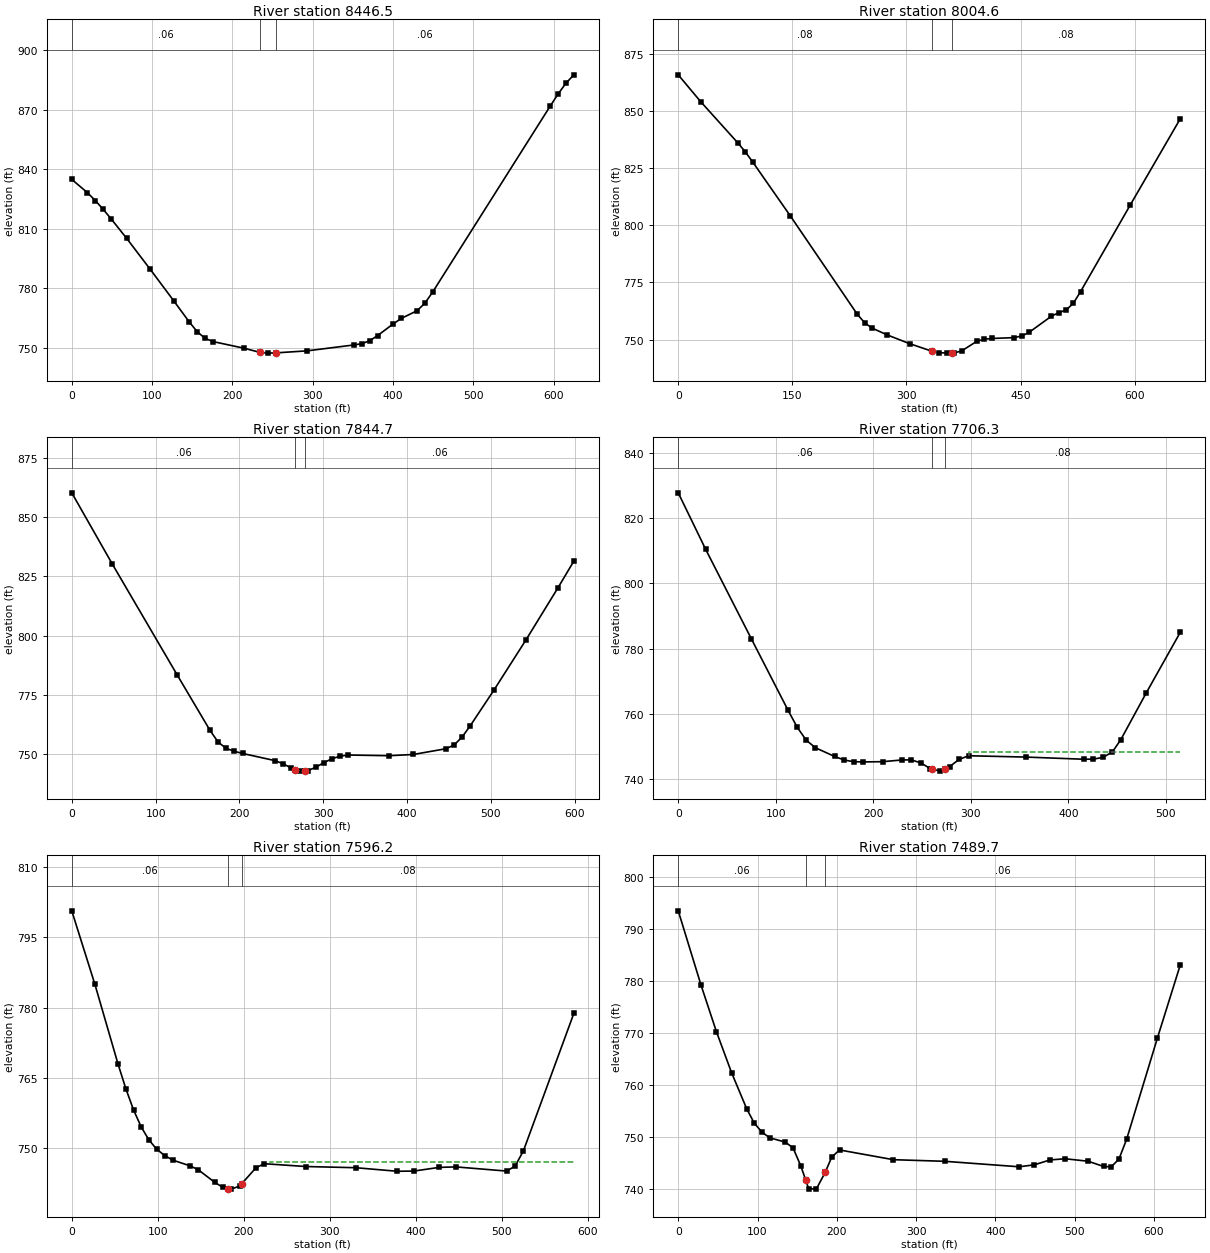
Type RM Length L Ch R = 1 ,8446.5  ,444.3,441.9,437.1
XS GIS Cut Line= 2
     1586131.769       388065.33     1585506.767      388076.539
#Sta/Elev= 30
       0  834.83    19.5  828.14    29.3  824.16    39.1  819.74    48.8  815.03
    68.4  805.06    97.7  789.46     127  773.56   146.5   762.8   156.3  757.94
     166  754.65   175.8  753.02   214.9  749.62     234747.5992   244.2  747.19
   254.8747.3339     293  748.34   351.6  751.33   361.4  751.98   371.2  753.51
   380.9  756.08   400.5  762.02   410.2  764.69   429.8  768.56   439.5  772.31
   449.3  777.98   595.8   871.9   605.6  878.01   615.3  883.38   625.1  887.59
#Mann= 3 , 0 , 0
       0     .06       0     234    .045       0   254.8     .06       0
Bank Sta=234,254.8
XS Rating Curve= 0 ,0
Exp/Cntr=0.3,0.1

Type RM Length L Ch R = 1 ,8004.6  ,165.6,160,153.4
XS GIS Cut Line= 3
     1586155.006      387603.068     1585655.028      387704.849
     1585514.706      387757.424
#Sta/Elev= 30
       0  865.75    29.4  854.06    78.5  835.94    88.3  832.02    98.1  827.55
   147.2  804.15   235.5  761.01   245.3  757.28   255.1  754.98   274.7  752.05
   304.2  748.22   333.1744.9705   343.4  744.31   353.2  744.08   359.6  744.13
     363  744.16   372.9  745.11   392.5  749.23   402.3  750.16   412.1  750.48
   441.6  750.86   451.4  751.55   461.2  753.14   490.6  760.22   500.4  761.78
   510.2  762.96   519.6  765.94     529     771   594.5  808.96   660.1  846.58
#Mann= 3 , 0 , 0
       0     .08       0   333.1    .045       0   359.6     .08       0
Bank Sta=333.1,359.6
XS Rating Curve= 0 ,0
Exp/Cntr=0.3,0.1

Type RM Length L Ch R = 1 ,7844.7  ,133.2,138.4,142.1
XS GIS Cut Line= 3
     1586045.121      387426.897     1585621.034      387594.536
     1585501.696      387673.145
#Sta/Elev= 30
       0   860.2    48.5   830.1   126.1  783.25   164.9   760.1   174.6  755.16
   184.4  752.47     194  751.28   203.8  750.37   242.6  747.34   252.3  745.99
     262   744.2   266.7743.5824   271.7  742.93   278.5  743.06   281.4  743.12
   291.1  744.55   300.8  746.52   310.5  748.17   320.2  749.25   329.9  749.72
   378.4  749.42   407.5  749.95   446.3  752.37     456  753.92   465.6   757.3
   475.1  761.93   503.6  777.08   541.8  798.23   579.9  820.15   598.9  831.43
#Mann= 3 , 0 , 0
       0     .06       0   266.7    .045       0   278.5     .06       0
Bank Sta=266.7,278.5
XS Rating Curve= 0 ,0
Exp/Cntr=0.3,0.1

Type RM Length L Ch R = 1 ,7706.3  ,106,110,115.9
XS GIS Cut Line= 4
      1585961.41      387357.088     1585827.982       387401.79
     1585530.552      387466.106     1585494.743      387525.838
#Sta/Elev= 30
       0  827.79    28.1  810.46      75  782.96   112.6  761.04     122  755.82
   131.3  751.84   140.7  749.55   160.4  746.87   170.2  745.78     180  745.27
   189.8   745.2   209.4  745.28   229.1   745.8   238.9  745.84   248.7  744.89
   258.5  743.15     260743.0322   268.3  742.38   273.5743.1107   278.1  743.75
     288  745.99   297.8   747.1   356.7  746.69   415.6  746.03   425.4  746.06
   435.2  746.58     445  748.24   453.7  752.04   479.8   766.4   514.7     785
#Mann= 3 , 0 , 0
       0     .06       0     260    .045       0   273.5     .08       0
#XS Ineff= 2 , 0
       0                  298.42       0  748.28
Permanent Ineff=
       F       F
Bank Sta=260,273.5
XS Rating Curve= 0 ,0
Exp/Cntr=0.3,0.1

Type RM Length L Ch R = 1 ,7596.2  ,113.9,106.5,93.7
XS GIS Cut Line= 4
     1585914.004      387345.111     1585815.392      387349.975
     1585539.004      387307.611     1585464.698      387499.277
#Sta/Elev= 30
       0  800.68    26.9  784.97    53.8  767.93    62.8   762.7    71.8  758.14
    80.8  754.46    89.8  751.69    98.7  749.74   108.4  748.31     118  747.36
   137.3  746.18   146.9  745.36   166.2  742.65   175.9  741.54   182.2  741.31
   185.5  741.19   195.2  741.85   197.7742.3487   214.4   745.8   224.1  746.62
   272.3  746.02   330.1  745.77   378.4  745.01   397.9  745.05   427.3  745.84
   446.9  745.94   505.6  745.05   515.4  746.07   525.2  749.35   583.9  778.76
#Mann= 3 , 0 , 0
       0     .06       0   182.2    .045       0   197.7     .08       0
#XS Ineff= 2 , 0
       0                     230       0     747
Permanent Ineff=
       F       F
Bank Sta=182.2,197.7
XS Rating Curve= 0 ,0
Exp/Cntr=0.3,0.1

Type RM Length L Ch R = 1 ,7489.7  ,72.2,72.2,203.4
XS GIS Cut Line= 5
     1585909.595      387282.868     1585818.454      387229.234
     1585672.825      387285.893      1585524.42      387293.722
     1585439.004      387499.277
#Sta/Elev= 30
       0  793.45    28.8  779.16    48.1  770.28    67.3  762.37    86.5  755.39
    96.1  752.65   105.8  750.94   115.5  749.87     135  749.06   144.8  747.94
   154.6  744.48   160.9   741.7   164.4  740.15   174.1  740.03   185.4743.2719
   193.6  746.18   203.4  747.55   271.3  745.68   336.3  745.37     430  744.32
   449.3   744.7   468.7  745.63     488  745.86   517.1  745.38   536.4  744.38
   546.1  744.31   555.8   745.8   565.5   749.6   604.2  768.98   633.2  783.09
#Mann= 3 , 0 , 0
       0     .06       0   160.9    .045       0   185.4     .06       0
Bank Sta=160.9,185.4
XS Rating Curve= 0 ,0
Exp/Cntr=0.3,0.1

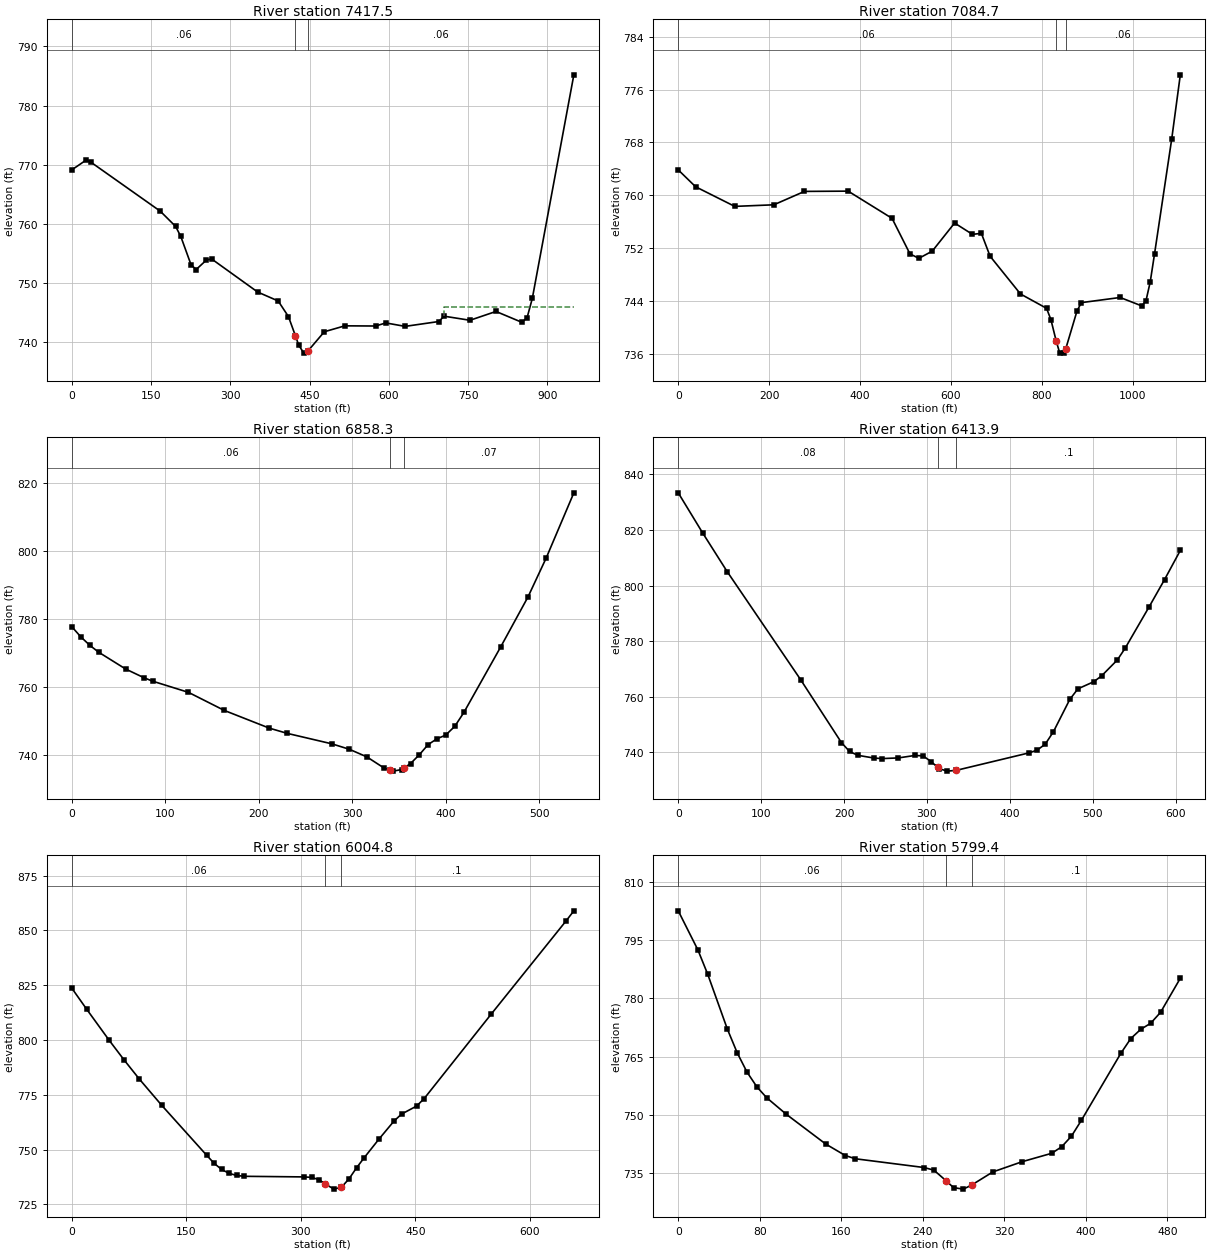
Type RM Length L Ch R = 1 ,7417.5  ,366.8,332.8,165.2
XS GIS Cut Line= 5
     1586131.666      387010.023     1586066.059      387055.904
     1585586.747      387241.988     1585486.799      387250.266
     1585400.937      387490.752
#Sta/Elev= 30
       0  769.15    26.7  770.78    35.6  770.49   167.4  762.18   196.5   759.6
   206.2  757.92   225.6  753.14   235.3  752.32   254.7  753.92   264.4  754.12
   351.7  748.52   390.5  747.01   409.9  744.38   423.1741.1388   429.3  739.56
     439   738.2   446.6  738.54   477.8  741.81   516.6  742.81   574.8  742.78
   594.2   743.3   630.7  742.72   694.5  743.54   704.3  744.44   753.4  743.75
   802.6  745.24   851.7   743.4   861.5  744.21   871.3  747.43   949.9  785.21
#Mann= 3 , 0 , 0
       0     .06       0   423.1    .045       0   446.6     .06       0
#XS Ineff= 2 , 0
       0                   704.3       0     746
Permanent Ineff=
       F       F
Bank Sta=423.1,446.6
XS Rating Curve= 0 ,0
Exp/Cntr=0.3,0.1

Type RM Length L Ch R = 1 ,7084.7  ,227.6,226.4,224.1
XS GIS Cut Line= 6
     1585987.365      386778.442     1585806.115      386885.386
     1585586.141      386982.726     1585380.539      387049.709
     1585443.832       387290.19     1585387.365      387470.803
#Sta/Elev= 30
       0  763.84    38.3  761.28   124.4  758.31   210.4  758.55   277.8  760.58
     374  760.62   470.6   756.5     510  751.12   529.6  750.44   559.1  751.53
   608.3  755.79   647.6  754.07   667.2  754.23   686.4  750.76   753.3  745.04
   810.7  742.87   820.3  741.15   831.7737.9727   839.4  736.16     849  736.08
     853736.7507   877.6  742.44   887.2  743.73   972.7  744.51    1020  743.24
  1029.4  743.97  1038.9  746.88  1048.4  751.13  1086.2  768.53  1105.1  778.24
#Mann= 3 , 0 , 0
       0     .06       0   831.7    .045       0     853     .06       0
Bank Sta=831.7,853
XS Rating Curve= 0 ,0
Exp/Cntr=0.3,0.1

Type RM Length L Ch R = 1 ,6858.3  ,438.9,444.4,450.2
XS GIS Cut Line= 4
     1585177.857      386988.023     1585206.449      387255.335
     1585250.105      387378.849     1585241.464      387515.714
#Sta/Elev= 30
       0  777.75     9.6  774.78    19.2  772.29    28.8  770.24    57.6  765.31
    76.8   762.8    86.4  761.74   124.8  758.45   163.2  753.13   211.2  747.94
   230.4   746.4   278.2  743.32   296.9  741.72   315.6  739.49   334.3  736.16
   340.5  735.59   343.7   735.3     353  735.77   355.5  736.24   362.4  737.54
   371.8  740.13   381.1  743.09   390.5  744.79   399.8  745.87   409.6  748.44
   419.4  752.55   458.6  771.72     488  786.51   507.6  798.04     537  817.08
#Mann= 3 , 0 , 0
       0     .06       0   340.5    .045       0   355.5     .07       0
Bank Sta=340.5,355.5
XS Rating Curve= 0 ,0
Exp/Cntr=0.3,0.1

Type RM Length L Ch R = 1 ,6413.9  ,396.6,409.1,420
XS GIS Cut Line= 3
     1584765.263      387000.255      1584811.16      387480.159
     1584888.957      387576.111
#Sta/Elev= 30
       0  833.35    29.5  818.91      59  805.04   147.6  766.19   196.8  743.57
   206.6  740.37   216.4  738.99   236.1  737.99     246   737.8   265.6  738.04
   285.3  738.92   295.2  738.78     305  736.73     313734.6239   314.8  734.15
   324.7  733.29   335.5733.5797   423.1  739.85   432.9  740.84   442.7  742.99
   452.6  747.49   472.3  759.08   482.1  762.88   501.1  765.42   510.6  767.52
   529.6  773.25   539.1   777.5   567.6  792.16   586.6  802.16   605.6  812.64
#Mann= 3 , 0 , 0
       0     .08       0     313    .045       0   335.5      .1       0
Bank Sta=313,335.5
XS Rating Curve= 0 ,0
Exp/Cntr=0.3,0.1

Type RM Length L Ch R = 1 ,6004.8  ,198.5,205.4,211.7
XS GIS Cut Line= 2
     1584585.449      386989.781     1584327.031      387594.309
#Sta/Elev= 30
       0   823.7    19.6  814.03    49.1  799.85    68.7  790.85    88.3  782.29
   117.8  770.23   176.6  747.46   186.4  743.79   196.2  740.97   206.1   739.2
   215.9  738.25   225.7  737.86   304.2  737.58     314  737.37   323.8   736.3
   331.8734.3489   343.4  732.01     352   732.8   353.2  732.91   363.1  736.74
   372.9  741.74   382.7  746.26   402.3  754.86   421.9  763.05   431.8  766.24
   451.4  769.88   461.2  773.22   549.5  811.98   647.6  854.53   657.4  858.96
#Mann= 3 , 0 , 0
       0     .06       0   331.8    .045       0     352      .1       0
Bank Sta=331.8,352
XS Rating Curve= 0 ,0
Exp/Cntr=0.3,0.1

Type RM Length L Ch R = 1 ,5799.4  ,323.1,311.7,299.9
XS GIS Cut Line= 3
     1584456.809      386981.914     1584209.148      387277.909
     1584204.031      387384.692
#Sta/Elev= 30
       0   802.6    19.3  792.51      29  786.19    48.2  772.09    57.9  765.95
    67.5  760.98    77.2  757.17    86.8  754.37   106.1  750.09   144.7  742.43
     164  739.45   173.7  738.62   241.2  736.36   250.9  735.68   262.9732.9468
   270.2  731.17   279.8  730.78   287.9731.8175   308.8  735.22   337.7  737.87
   366.6  740.03   376.3   741.7   385.9  744.43   395.7  748.54   434.5  765.86
   444.2  769.64     454  772.03   463.7  773.58   473.4   776.4   492.8   785.2
#Mann= 3 , 0 , 0
       0     .06       0   262.9    .045       0   287.9      .1       0
Bank Sta=262.9,287.9
XS Rating Curve= 0 ,0
Exp/Cntr=0.3,0.1

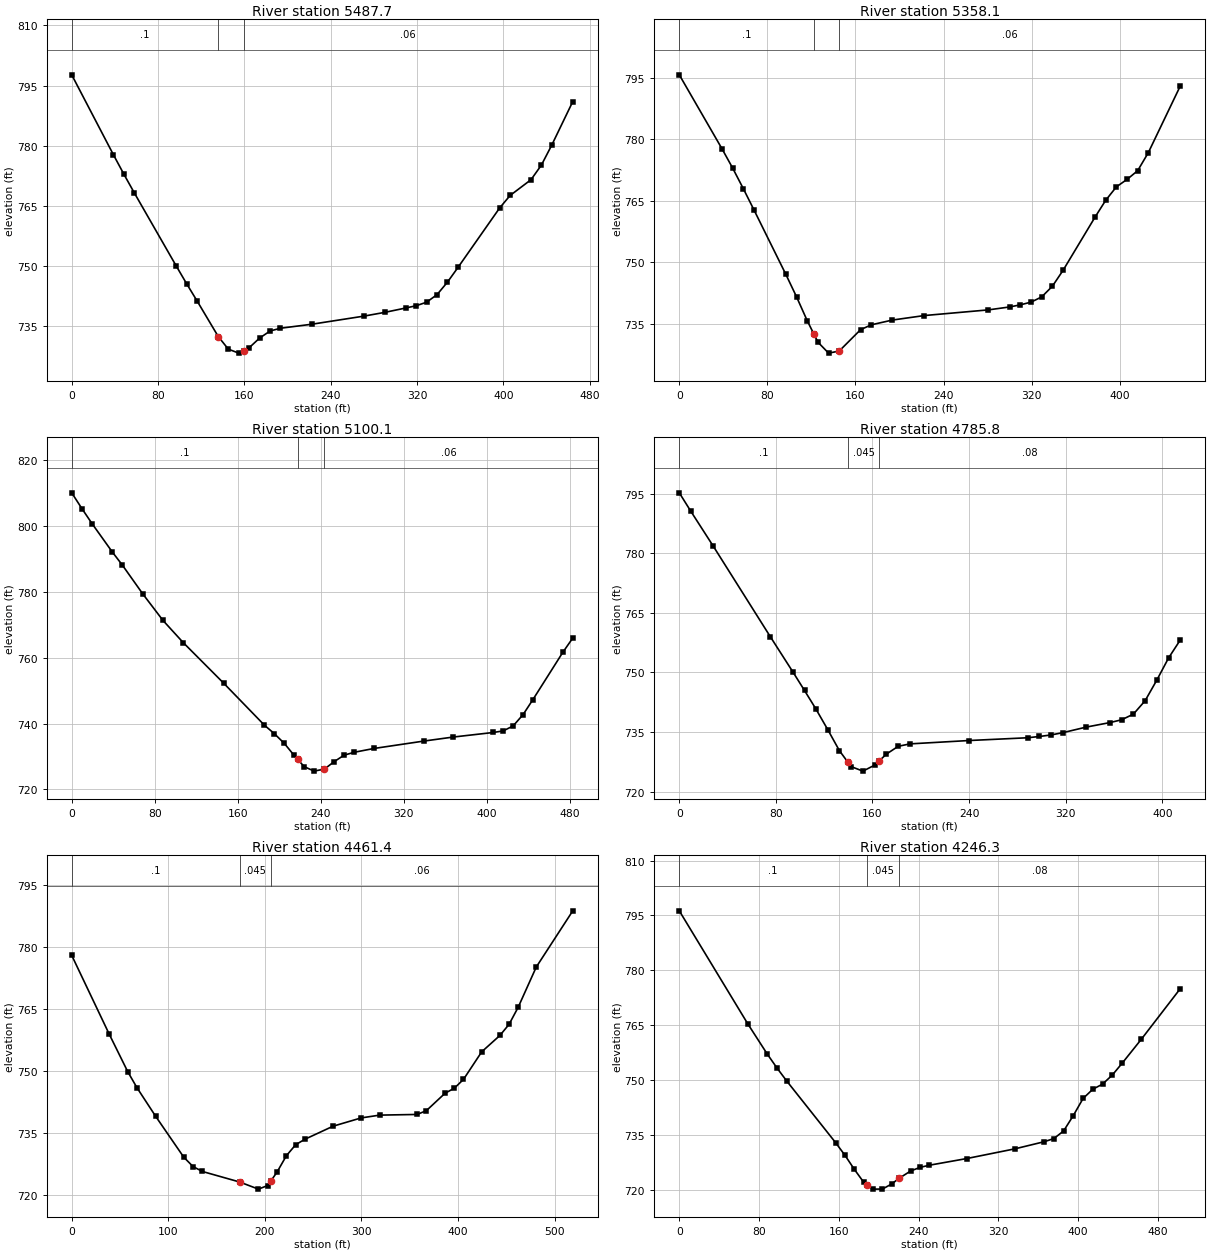
Type RM Length L Ch R = 1 ,5487.7  ,128.7,129.6,130.6
XS GIS Cut Line= 2
     1584029.426      386918.785     1583944.315      387375.179
#Sta/Elev= 30
       0  797.69    38.7  777.75    48.4   772.9      58  768.28    96.7  750.14
   106.4  745.68   116.1  741.39   135.8732.4852   145.1  729.35   154.8  728.36
   159.3  728.99   164.4   729.7   174.1  732.11   183.8  733.87   193.4  734.56
   222.5  735.56   270.8  737.58   290.2  738.52   309.5   739.6   319.2  740.17
   328.8  741.04   338.5  742.93   348.2  746.06   357.9   749.7   396.6  764.55
   406.2  767.63   425.6  771.57   435.2   775.2   444.9  780.23   464.3  791.04
#Mann= 3 , 0 , 0
       0      .1       0   135.8    .045       0   159.3     .06       0
Bank Sta=135.8,159.3
XS Rating Curve= 0 ,0
Exp/Cntr=0.3,0.1

Type RM Length L Ch R = 1 ,5358.1  ,257,257.9,258.9
XS GIS Cut Line= 2
     1583905.639      386907.408     1583803.761      387350.921
#Sta/Elev= 30
       0  795.72    38.7  777.72    48.4  773.01    58.1  767.98    67.8  762.79
    96.8  747.04   106.5  741.57   116.2  735.74   122.2732.5112   125.9  730.52
   135.6  727.84   145.2  728.34   164.6  733.55   174.3  734.74   193.6  735.91
   222.7  737.01   280.8  738.39   300.2  739.11   309.8  739.62   319.5  740.28
   329.2  741.56   338.9  744.17   348.6  748.05   377.6  761.01   387.3  765.12
     397   768.4   406.6   770.2   416.3  772.33     426  776.74   455.1  793.04
#Mann= 3 , 0 , 0
       0      .1       0   122.2    .045       0   145.2     .06       0
Bank Sta=122.2,145.2
XS Rating Curve= 0 ,0
Exp/Cntr=0.3,0.1

Type RM Length L Ch R = 1 ,5100.1  ,329.3,314.3,298.9
XS GIS Cut Line= 3
     1583785.934      386821.655     1583637.287      386932.946
     1583558.797      387219.592
#Sta/Elev= 30
       0  810.14     9.8  805.36    19.6  800.78    39.1  792.17    48.9  788.14
    68.4  779.46      88  771.35   107.5  764.62   146.6  752.25   185.7  739.54
   195.3  736.95   204.9     734   214.4  730.34   217.6  729.21     224  726.95
   233.6  725.58   243.6726.2162   252.8  728.43   262.4  730.41     272  731.29
   291.2  732.46   339.1   734.7   367.8  735.94   406.2  737.32   415.8   737.8
   425.4  739.31     435  742.76   444.5  747.33   473.3  761.68   482.9  766.02
#Mann= 3 , 0 , 0
       0      .1       0   217.6    .045       0   243.6     .06       0
Bank Sta=217.6,243.6
XS Rating Curve= 0 ,0
Exp/Cntr=0.3,0.1

Type RM Length L Ch R = 1 ,4785.8  ,324.8,324.4,323.5
XS GIS Cut Line= 3
       1583292.4      386821.098     1583304.206      386933.598
     1583422.435      387211.376
#Sta/Elev= 30
       0  795.21     9.4  790.64    28.3   781.7    75.4  758.98    94.3  750.01
   103.7  745.45   113.1  740.81   122.9  735.62   132.6   730.3   139.6 727.399
   142.3  726.28   152.1  725.14   161.8  726.65   165.6727.7319   171.6  729.44
   181.3  731.39     191     732   239.7  732.84   288.4  733.54   298.2  733.86
   307.9  734.25   317.6  734.82   337.1  736.23   356.6  737.36   366.3  738.06
   376.1  739.49   385.8  742.86   395.5  748.06   405.3  753.67     415  758.19
#Mann= 3 , 0 , 0
       0      .1       0   139.6    .045       0   165.6     .08       0
Bank Sta=139.6,165.6
XS Rating Curve= 0 ,0
Exp/Cntr=0.3,0.1

Type RM Length L Ch R = 1 ,4461.4  ,215.9,215.2,215.5
XS GIS Cut Line= 3
       1582943.4      386926.593     1583109.124      387286.471
     1583077.817      387404.952
#Sta/Elev= 30
       0     778    38.6  759.05      58  749.87    67.6  745.97      87  739.04
     116  729.19   125.6  726.92   135.3  725.73   173.9  723.18   193.3  721.46
   202.9  722.33   206.5723.5417   212.6  725.59   222.3  729.55   231.9  732.21
   241.6  733.54   270.6  736.68   299.6  738.68   318.9  739.36   357.6  739.52
   367.2  740.44   386.5  744.64   396.2  745.88   405.6  747.99   424.5  754.67
   443.3  758.62   452.8  761.31   462.2  765.42     481  775.18   518.8  788.77
#Mann= 3 , 0 , 0
       0      .1       0   173.9    .045       0   206.5     .06       0
Bank Sta=173.9,206.5
XS Rating Curve= 0 ,0
Exp/Cntr=0.3,0.1

Type RM Length L Ch R = 1 ,4246.3  ,143.4,145.3,144.7
XS GIS Cut Line= 4
     1582761.107      386951.806     1582798.134      387094.316
     1582868.249      387238.281     1582924.128      387425.358
#Sta/Elev= 30
       0  796.25    68.7  765.35    88.3  757.06    98.2   753.2     108  749.64
   156.7   732.9   166.1  729.44   175.5   725.6   184.9  722.07   188.2   721.4
   194.3  720.16   203.8  720.18   213.2   721.6   220.2 723.067     232  725.11
   241.4   726.1   250.9   726.7   288.5  728.53   336.7  731.18     366  733.12
   375.7  733.98   385.5  736.07   395.2  740.26     405  744.94   414.8  747.48
   424.5  748.86   434.3  751.34     444  754.51   463.6  761.19   502.6     775
#Mann= 3 , 0 , 0
       0      .1       0   188.2    .045       0   220.2     .08       0
Bank Sta=188.2,220.2
XS Rating Curve= 0 ,0
Exp/Cntr=0.3,0.1

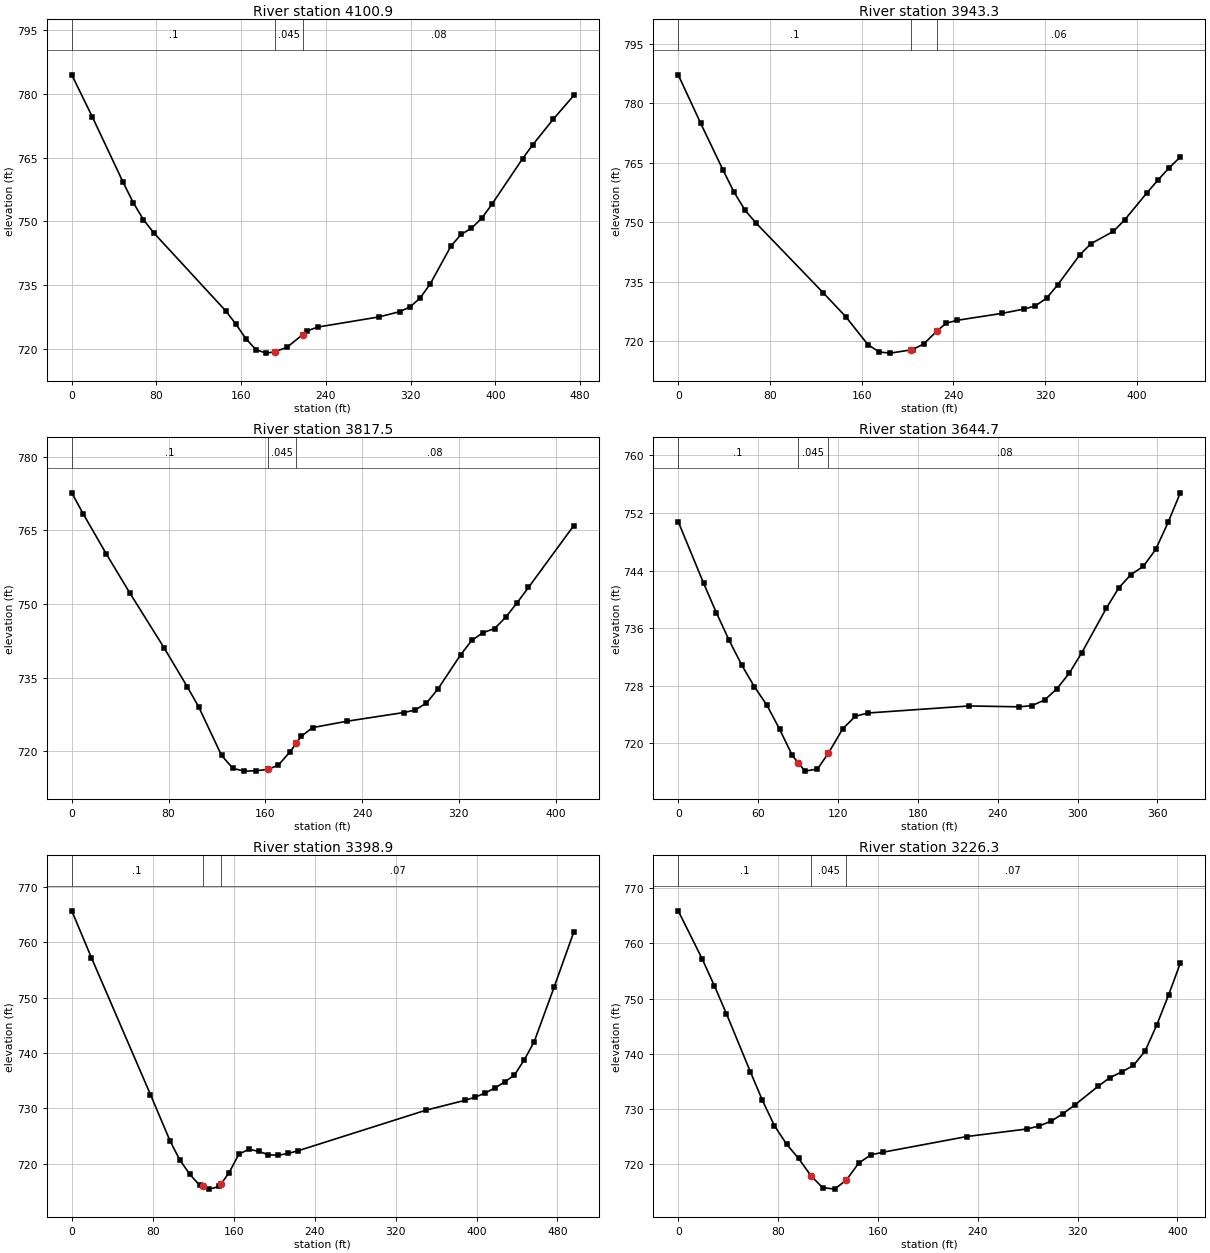
Type RM Length L Ch R = 1 ,4100.9  ,155.8,157.7,159
XS GIS Cut Line= 2
     1582637.872      387037.066     1582808.385       387479.54
#Sta/Elev= 30
       0  784.53    19.4  774.63    48.4  759.25    58.1  754.39    67.7  750.38
    77.4   747.3   145.2  728.95   154.8  725.85   164.5  722.32   174.2   719.7
   183.9  718.94   191.7  719.26   203.2   720.3   218.2723.3164   222.6  724.21
   232.3  725.08   290.3  727.48   309.7  728.71   319.4  729.82     329  731.91
   338.7  735.32   358.1  744.15   367.7  746.92   377.4  748.36   387.1  750.69
   396.8  754.02   425.8  764.78   435.5  768.08   454.8  774.08   474.2  779.69
#Mann= 3 , 0 , 0
       0      .1       0   191.7    .045       0   218.2     .08       0
Bank Sta=191.7,218.2
XS Rating Curve= 0 ,0
Exp/Cntr=0.3,0.1

Type RM Length L Ch R = 1 ,3943.3  ,121.2,125.8,128.7
XS GIS Cut Line= 2
     1582505.595      387091.063     1582634.935      387509.466
#Sta/Elev= 30
       0  787.16    19.5  774.98    38.9  763.25    48.7  757.55    58.4  752.96
    68.1   749.7   126.5  732.18     146  726.19   165.4  719.14   175.2  717.26
   184.9  716.97     203717.7906   204.4  717.87   214.1  719.29   225.5722.4998
   233.6   724.5   243.3  725.25   282.2  726.99   301.7  728.09   311.4  728.88
   321.2  730.81   330.9  734.17   350.4  741.82   360.1  744.59   379.6  747.69
   389.3  750.55   408.7  757.37   418.5  760.66   428.2  763.71   437.9  766.44
#Mann= 3 , 0 , 0
       0      .1       0     203    .045       0   225.5     .06       0
Bank Sta=203,225.5
XS Rating Curve= 0 ,0
Exp/Cntr=0.3,0.1

Type RM Length L Ch R = 1 ,3817.5  ,170.1,172.8,176
XS GIS Cut Line= 4
     1582406.304      387164.247     1582440.812      387243.136
     1582470.421      387429.162     1582521.756      387560.081
#Sta/Elev= 30
       0  772.64     9.6  768.29    28.7  760.13    47.8  752.31    76.5  740.99
    95.5  733.13   104.9  729.04   123.8  719.15   133.2  716.51   142.6  715.94
     152  716.01   162.3 716.291   170.9  717.19   180.3  719.82   185.5721.5902
   189.7  723.02   199.1  724.81   227.4   726.1   274.5  727.88   283.8  728.38
   293.2   729.8   302.6  732.62   321.4  739.61   330.7  742.57   340.1  744.17
   349.5  744.97   358.8   747.3   368.2  750.25   377.6  753.36   415.1  765.98
#Mann= 3 , 0 , 0
       0      .1       0   162.3    .045       0   185.5     .08       0
Bank Sta=162.3,185.5
XS Rating Curve= 0 ,0
Exp/Cntr=0.3,0.1

Type RM Length L Ch R = 1 ,3644.7  ,246.5,245.8,244.2
XS GIS Cut Line= 4
     1582308.198      387229.136     1582281.123      387279.582
     1582283.889      387497.522     1582315.837      387594.414
#Sta/Elev= 30
       0   750.8    19.1  742.22    28.6  738.17    38.2  734.32    47.7  730.87
    57.2  727.86    66.7  725.26    76.2  721.93    85.7   718.3      90717.3162
    95.2  716.12   104.6  716.42   112.8718.6121   123.6  722.01   133.1  723.75
   142.5   724.2   218.4  725.18   256.3  725.06   265.7  725.23   275.2     726
   284.5  727.57   293.8  729.75     303  732.52   321.6  738.76   330.9  741.58
   340.1  743.45   349.4  744.58   358.7  746.94     368  750.69   377.2  754.81
#Mann= 3 , 0 , 0
       0      .1       0      90    .045       0   112.8     .08       0
Bank Sta=90,112.8
XS Rating Curve= 0 ,0
Exp/Cntr=0.3,0.1

Type RM Length L Ch R = 1 ,3398.9  ,164.3,172.6,180.8
XS GIS Cut Line= 3
     1582031.089      387195.293     1582057.793      387631.899
     1582090.838       387680.56
#Sta/Elev= 30
       0  765.72    19.4  757.26    77.8   732.5    97.2  724.11   106.9  720.64
   116.6  718.13   126.4   716.1   129.2715.9044   136.1  715.42   145.8   715.9
   147.7  716.39   155.5   718.4   165.2  721.75     175  722.62   184.7  722.25
   194.4  721.62   204.1  721.55   213.8  721.86   223.6  722.35   349.9  729.68
   388.8  731.48   398.5  732.03   408.3  732.77     418  733.68   427.7  734.78
   437.4  736.01   447.2  738.78     457  742.06   476.6  751.88   496.2  761.92
#Mann= 3 , 0 , 0
       0      .1       0   129.2    .045       0   147.7     .07       0
Bank Sta=129.2,147.7
XS Rating Curve= 0 ,0
Exp/Cntr=0.3,0.1

Type RM Length L Ch R = 1 ,3226.3  ,153.5,159.8,166
XS GIS Cut Line= 3
      1581908.88      387180.692      1581819.26      387465.839
     1581746.654      387539.588
#Sta/Elev= 30
       0  765.92    19.3  757.14    28.9  752.35    38.6  747.26    57.8  736.71
    67.5  731.51    77.1  726.92    86.8  723.58    96.4  720.99   106.7717.7429
   115.7  715.69   125.3  715.41   134.7717.0381   144.6  720.12   154.3  721.62
   163.9   722.1   231.4  724.96   279.6  726.33   289.3  726.87   298.9  727.75
   308.3   729.1   317.7  730.66   336.5  734.07   345.9  735.64   355.4  736.67
   364.8  737.85   374.2  740.47   383.6  745.24     393  750.65   402.4  756.42
#Mann= 3 , 0 , 0
       0      .1       0   106.7    .045       0   134.7     .07       0
Bank Sta=106.7,134.7
XS Rating Curve= 0 ,0
Exp/Cntr=0.3,0.1