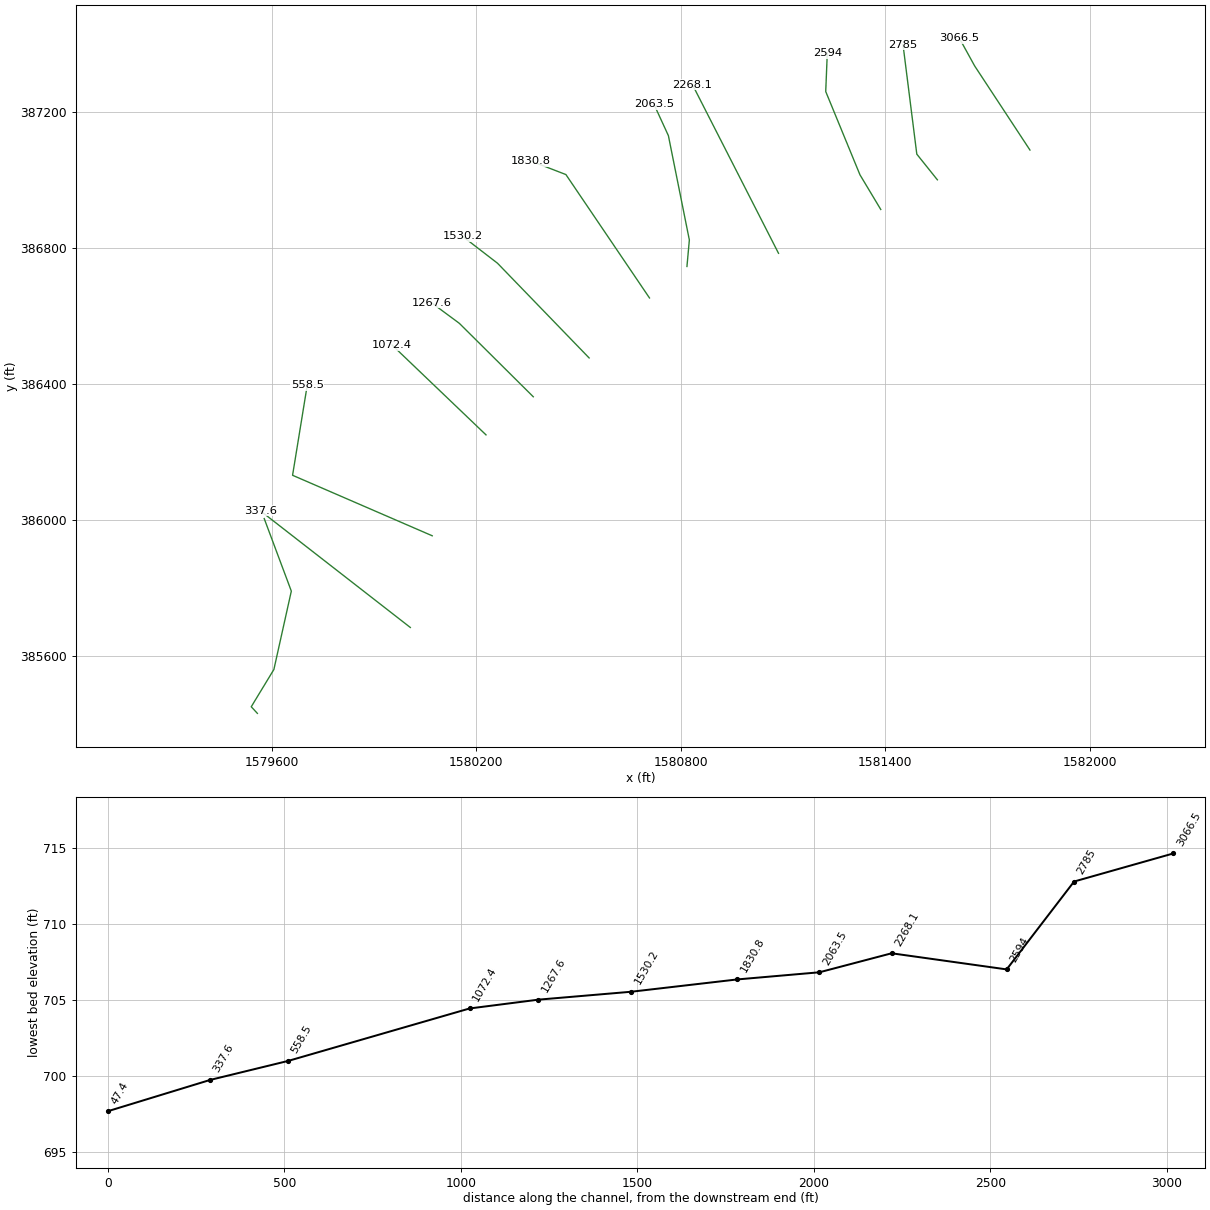
HEC-RAS study TENMLRUN.prj: TENMLRUN

--- TENMLRUN.g01 (geometry) --- (continued)

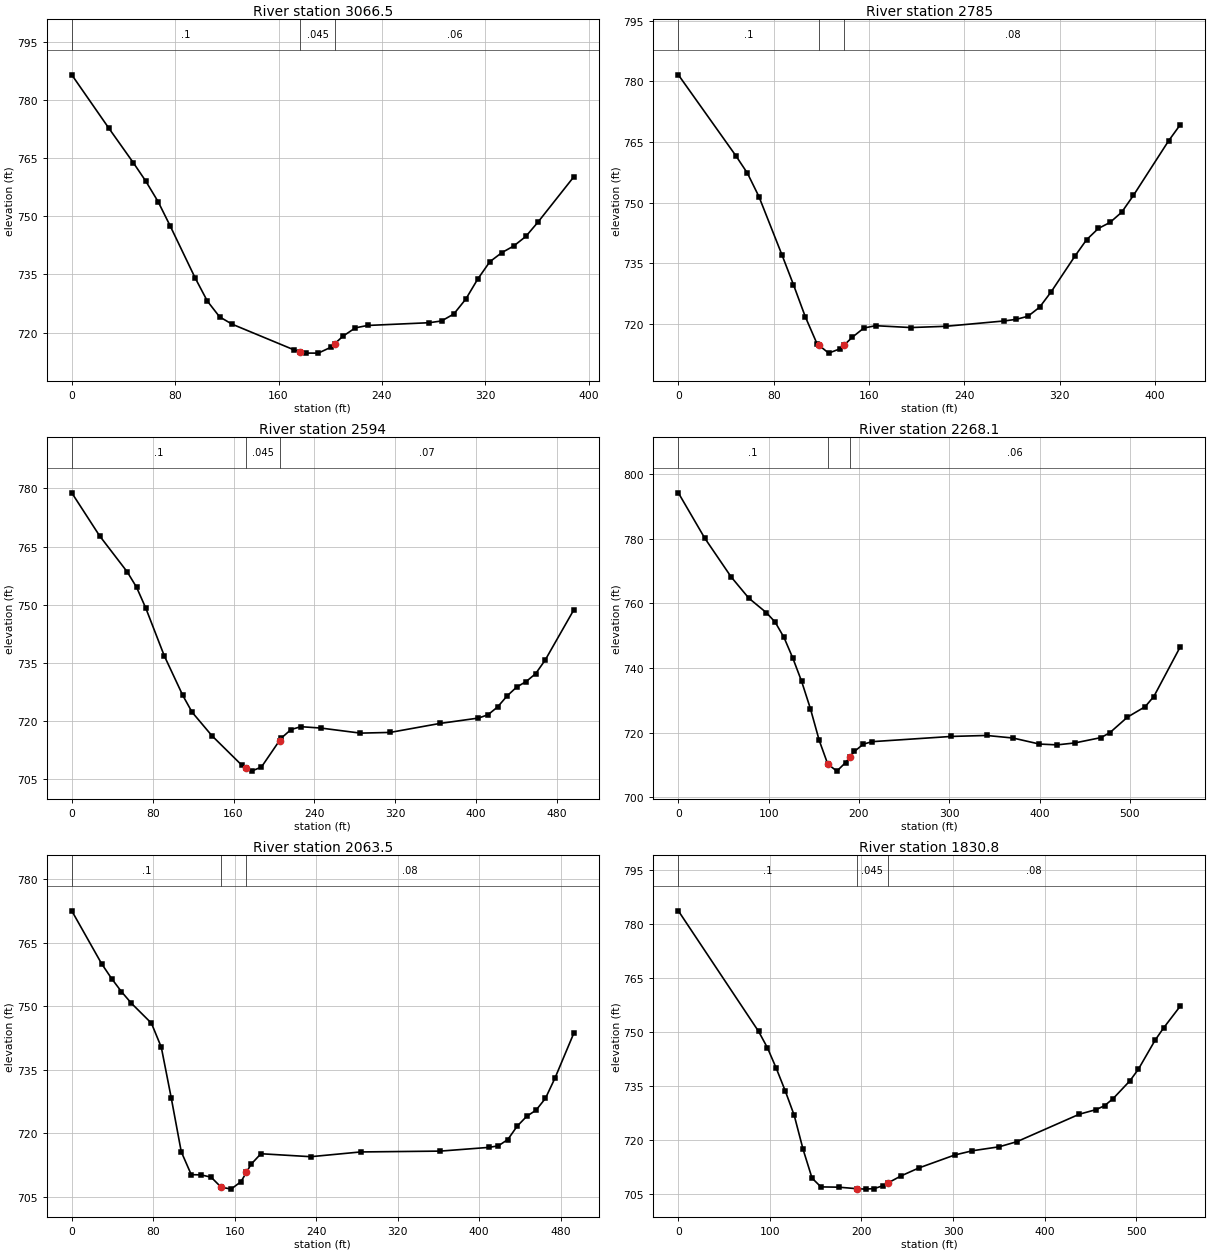
Type RM Length L Ch R = 1 ,3066.5  ,292.3,281.5,270.8
XS GIS Cut Line= 3
     1581824.865      387088.164     1581662.682      387335.361
      1581617.92      387416.636
#Sta/Elev= 30
       0  786.59    28.6  772.84    47.7  763.84    57.2  759.15    66.8  753.82
    76.3  747.44    95.4  734.15   104.9  728.12   114.4  724.04     124  722.16
   171.7  715.55   176.8715.0829   181.2  714.68   190.7  714.67   200.3  716.16
   203.6 717.157   209.8  719.03   219.4   721.2   228.9  721.82   276.6  722.53
   286.1  722.98   295.6  724.78   304.9  728.64   314.2  733.85   323.5  738.29
   332.8  740.65     342  742.36   351.3  744.82   360.6  748.47   388.4  760.21
#Mann= 3 , 0 , 0
       0      .1       0   176.8    .045       0   203.6     .06       0
Bank Sta=176.8,203.6
XS Rating Curve= 0 ,0
Exp/Cntr=0.3,0.1

Type RM Length L Ch R = 1 ,2785    ,184.9,191,196.8
XS GIS Cut Line= 3
     1581553.253      387000.622     1581492.888      387076.097
     1581452.382      387397.987
#Sta/Elev= 30
       0  781.59    48.3  761.57      58  757.26    67.6   751.5      87  737.04
    96.6  729.71   106.5  721.81   116.3  715.16   117.8   714.8   126.1  712.82
     136  713.93   139.3714.8661   145.8  716.71   155.6  719.02   165.5   719.6
     195  719.14   224.4  719.45   273.6  720.78   283.4  721.17   293.3  721.93
   303.1  724.18   312.9  728.03   332.6  736.75   342.4  740.82   352.3  743.62
   362.1  745.11   371.9  747.63   381.8  751.81   411.2  765.25   421.1  769.28
#Mann= 3 , 0 , 0
       0      .1       0   117.8    .045       0   139.3     .08       0
Bank Sta=117.8,139.3
XS Rating Curve= 0 ,0
Exp/Cntr=0.3,0.1

Type RM Length L Ch R = 1 ,2594    ,323.8,325.9,327.5
XS GIS Cut Line= 4
     1581387.139      386913.425     1581326.028      387015.508
     1581225.653      387260.221     1581230.195      387373.147
#Sta/Elev= 30
       0  778.88    27.5  767.79    54.9  758.46    64.1   754.5    73.2  749.13
    91.5  736.81   109.8  726.59     119  722.26   138.6  716.19     168  708.62
   172.8 707.844   177.8  707.04   187.6   708.1   205.5 714.928   207.1  715.54
   216.9  717.78   226.7  718.51   246.3  718.16   285.5  716.85   314.9  717.03
   363.9  719.34   402.3  720.74   411.7  721.59   421.2  723.61   430.6  726.45
     440  728.73   449.4  730.16   458.8  732.19   468.2  735.68   496.5  748.64
#Mann= 3 , 0 , 0
       0      .1       0   172.8    .045       0   205.5     .07       0
Bank Sta=172.8,205.5
XS Rating Curve= 0 ,0
Exp/Cntr=0.3,0.1

Type RM Length L Ch R = 1 ,2268.1  ,210.6,204.6,198.3
XS GIS Cut Line= 2
     1581087.126      386784.568     1580834.923       387279.81
#Sta/Elev= 30
       0  794.17    29.2  780.17    58.5  768.15      78   761.6    97.5   757.1
   107.2  754.18     117  749.43   126.8  743.02   136.5  735.86   146.2  727.44
     156  717.59   165.4   710.3   175.5   708.1   185.2  710.76   189.9712.4146
     195  714.21   204.8  716.43   214.5  717.21   302.3  718.83   341.3  719.13
   370.5  718.34   399.8  716.47   419.3  716.22   438.8  716.81     468  718.47
   477.8  719.99   497.3  724.81   516.8  728.01   526.5  731.18   555.8  746.58
#Mann= 3 , 0 , 0
       0      .1       0   165.4    .045       0   189.9     .06       0
Bank Sta=165.4,189.9
XS Rating Curve= 0 ,0
Exp/Cntr=0.3,0.1

Type RM Length L Ch R = 1 ,2063.5  ,223.7,232.8,241.6
XS GIS Cut Line= 4
     1580818.457      386745.845     1580825.517      386823.675
     1580764.013      387130.523     1580721.582      387222.928
#Sta/Elev= 30
       0  772.58    29.3  760.09    39.1  756.59    48.8  753.48    58.6  750.73
    78.2  746.04    87.9  740.36    97.7  728.35   107.5  715.67   117.3  710.27
     127  710.21   136.8  709.67   146.5  707.34   156.4  706.85   166.2  708.63
   171.5710.8365     176  712.71   185.7  715.21   234.6  714.51   283.5  715.63
   361.8  715.83   409.6  716.71   418.8  717.08   428.1  718.57   437.3  721.73
   446.6  724.04   455.8   725.5     465  728.28   474.3  733.03   492.8  743.64
#Mann= 3 , 0 , 0
       0      .1       0   146.5    .045       0   171.5     .08       0
Bank Sta=146.5,171.5
XS Rating Curve= 0 ,0
Exp/Cntr=0.3,0.1

Type RM Length L Ch R = 1 ,1830.8  ,296.1,300.5,304.5
XS GIS Cut Line= 3
     1580708.528      386653.278     1580463.285      387016.101
     1580360.413      387055.933
#Sta/Elev= 30
       0  783.61    87.6  750.16    97.3  745.61     107  739.88   116.8   733.6
   126.5  726.89   136.2  717.44     146  709.44   155.7     707   175.2  706.92
   194.6  706.51   204.4  706.38   214.1  706.54   223.8  707.36   229.2 708.137
   243.3  710.06   262.8  712.27   301.7  715.84   321.2  717.03   350.4  718.13
   369.8  719.55   437.9  727.17   456.3  728.45   465.5  729.54   474.7  731.47
   493.1  736.42   502.3  739.61   520.7  747.72   529.9   751.1   548.2  757.18
#Mann= 3 , 0 , 0
       0      .1       0   194.6    .045       0   229.2     .08       0
Bank Sta=194.6,229.2
XS Rating Curve= 0 ,0
Exp/Cntr=0.3,0.1

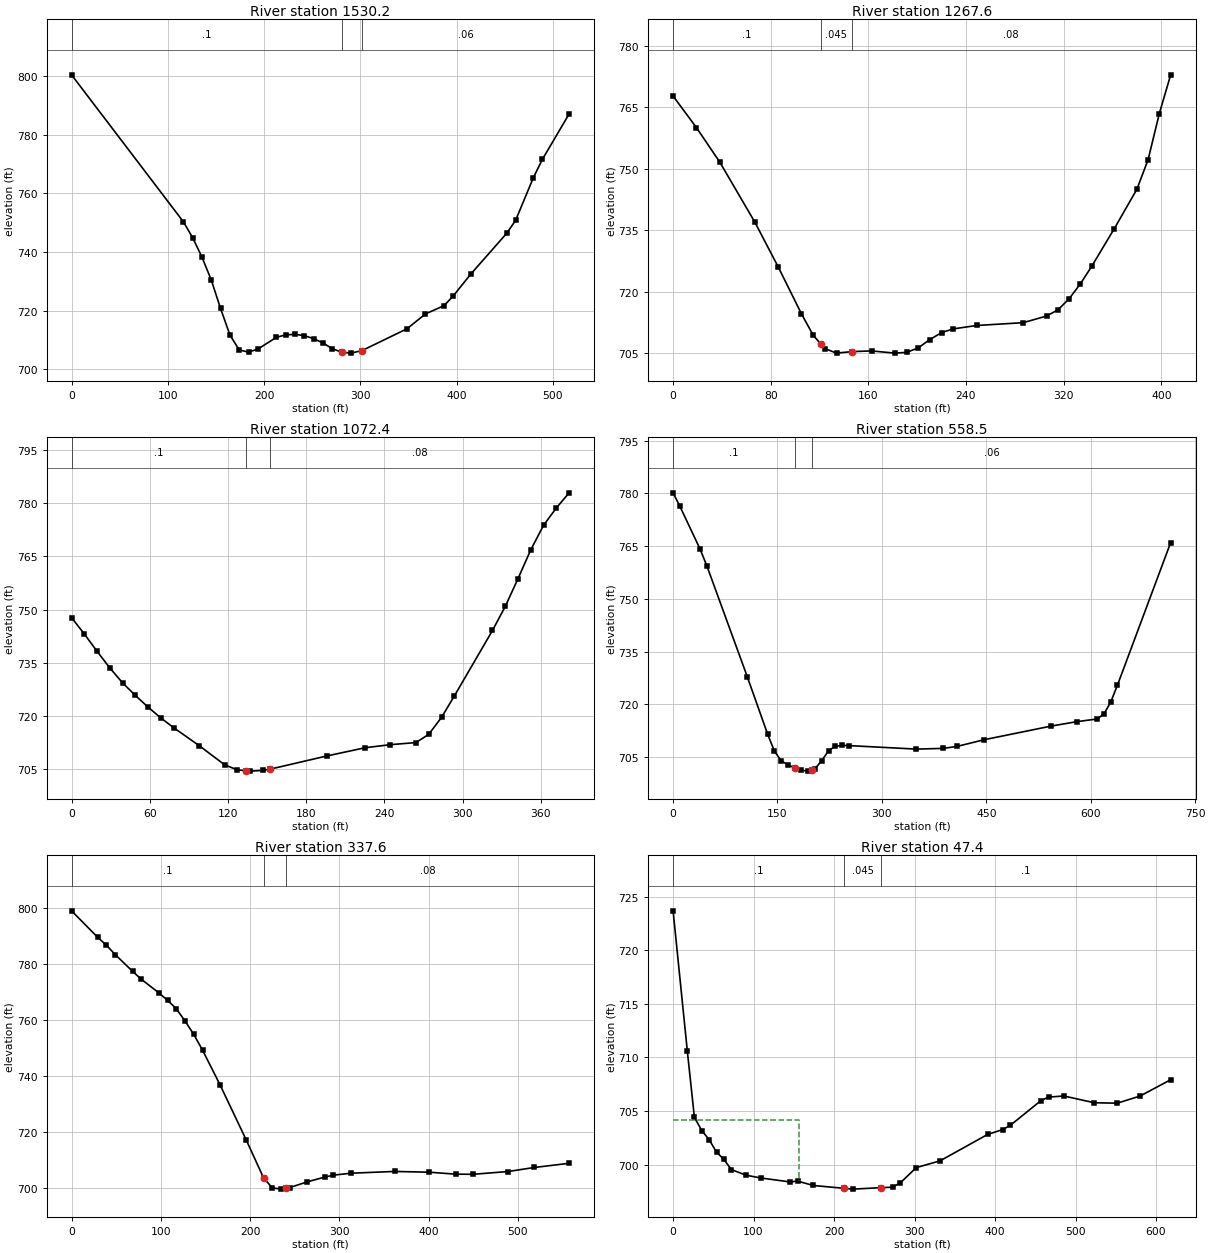
Type RM Length L Ch R = 1 ,1530.2  ,260.9,262.6,262.1
XS GIS Cut Line= 3
     1580531.434      386476.902     1580262.588      386755.402
     1580159.709        386834.8
#Sta/Elev= 30
       0  800.36   116.1  750.35   125.8  744.92   135.5  738.26   145.2  730.46
   154.8  720.81   164.5  711.79   174.2  706.65   183.9  705.92   193.6  706.95
   212.9  710.96   222.6  711.79   232.3  711.97   241.9  711.52   251.6  710.49
   261.3  709.02     271  707.07   280.6   705.9   290.3  705.57   301.8706.4386
   348.4  713.84   367.7  718.91   387.1  721.75   396.4  724.98   414.9  732.52
   452.1  746.37   461.4  750.81   479.9  765.38   489.2  771.57     517  787.04
#Mann= 3 , 0 , 0
       0      .1       0   280.6    .045       0   301.8     .06       0
Bank Sta=280.6,301.8
XS Rating Curve= 0 ,0
Exp/Cntr=0.3,0.1

Type RM Length L Ch R = 1 ,1267.6  ,194.9,195.2,194.4
XS GIS Cut Line= 3
     1580367.544      386362.777     1580150.634      386578.673
     1580068.954      386639.184
#Sta/Elev= 30
       0  767.77    19.1  760.08    38.3  751.63      67     737    86.1   726.1
   105.2  714.63   114.8  709.42   120.9707.3331   124.3  706.17   133.9  705.05
   146.4705.4194   162.6  705.59   181.7  705.05   191.3  705.23   200.8  706.31
   210.4  708.37     220  710.06   229.5  710.96   248.7  711.79   286.9  712.48
     306   714.1   315.3   715.6   324.5  718.31   333.8  721.99     343  726.23
   361.5  735.42     380  745.01   389.2  752.24   398.4   763.5   407.7  772.94
#Mann= 3 , 0 , 0
       0      .1       0   120.9    .045       0   146.4     .08       0
Bank Sta=120.9,146.4
XS Rating Curve= 0 ,0
Exp/Cntr=0.3,0.1

Type RM Length L Ch R = 1 ,1072.4  ,501.3,513.9,523.6
XS GIS Cut Line= 2
     1580228.854      386250.722     1579953.319      386514.807
#Sta/Elev= 30
       0  747.73     9.8  743.14    19.6  738.23    29.4  733.54    39.1  729.37
    48.9  725.82    58.7  722.51    68.5  719.46    78.3  716.72    97.9  711.66
   117.4  706.26   127.2  704.81   133.6  704.59     137  704.47   146.8  704.68
   151.9 704.988   195.7  708.73   225.1  711.06   244.6  711.93   264.2  712.52
     274  714.84   283.8  719.62   293.6  725.63   322.9  744.12   332.7   750.9
   342.5  758.74   352.3  766.88   362.1  773.78   371.9  778.67   381.7  782.92
#Mann= 3 , 0 , 0
       0      .1       0   133.6    .045       0   151.9     .08       0
Bank Sta=133.6,151.9
XS Rating Curve= 0 ,0
Exp/Cntr=0.3,0.1

Type RM Length L Ch R = 1 ,558.5   ,226.3,220.9,214.8
XS GIS Cut Line= 3
     1580071.063      385954.025     1579661.317        386131.9
     1579704.337      386396.684
#Sta/Elev= 30
       0  780.15     9.7  776.35    38.8  764.15    48.6  759.35   106.8  727.75
     136  711.44   145.7  706.66   155.4  703.96   165.1  702.81   174.8  701.93
   184.5  701.27   194.2  701.02   200.3701.4624   203.9  701.72   213.6     704
   223.3  706.81   233.1   708.1   242.8  708.33   252.5  708.28   349.6  707.28
   388.4  707.49   407.8  708.04   446.7  709.94   542.5   713.8   580.8  715.11
   609.6  715.85   619.1   717.3   628.7  720.64   638.3  725.39   714.9  766.01
#Mann= 3 , 0 , 0
       0      .1       0   174.8    .045       0   200.3     .06       0
Bank Sta=174.8,200.3
XS Rating Curve= 0 ,0
Exp/Cntr=0.3,0.1

Type RM Length L Ch R = 1 ,337.6   ,324.2,290.2,243
XS GIS Cut Line= 2
     1580006.802      385684.412     1579567.217      386027.116
#Sta/Elev= 30
       0  798.94    29.3   789.5    39.1  786.67    48.9  783.36    68.4  777.37
    78.2  774.54    97.8  769.71   107.6  767.02   117.3  764.06   127.1  759.69
   136.9   754.9   146.7  749.32   166.2  737.02   195.6  717.35   215.1  703.78
   224.9  700.22   234.7  699.77   240.1  700.08   244.5  700.33     264  702.36
   283.6  704.06   293.4  704.75   312.9  705.44   361.8  706.07   400.9   705.8
   430.3   705.1   449.8  705.06   488.9  706.04   518.3  707.48   557.4  708.97
#Mann= 3 , 0 , 0
       0      .1       0   215.1    .045       0   240.1     .08       0
Bank Sta=215.1,240.1
XS Rating Curve= 0 ,0
Exp/Cntr=0.3,0.1

Type RM Length L Ch R = 1 ,47.4    ,15.6,47.4,90
XS GIS Cut Line= 5
      1579558.06      385431.827     1579540.084      385451.312
     1579606.491      385560.906     1579657.653      385791.316
     1579578.135      386004.537
#Sta/Elev= 30
       0  723.68    17.7  710.59    26.5   704.4    35.7  703.17    44.8  702.33
      54  701.16    63.1  700.49    72.3  699.54    90.6  699.01   108.9  698.75
   145.5  698.38   154.6  698.46   174.3  698.05   212.3697.7856   223.5  697.71
   258.6697.8486   272.7  697.89   282.5  698.31   302.2  699.72   331.7  700.35
   390.7  702.81   409.6  703.27   419.1  703.67     457  705.97   466.5   706.3
   485.5   706.4   523.4  705.77   551.9  705.73   580.3   706.4   618.2  707.92
#Mann= 3 , 0 , 0
       0      .1       0   212.3    .045       0   258.6      .1       0
#XS Ineff= 2 , 0
          156.16  704.15
Permanent Ineff=
       F       F
Bank Sta=212.3,258.6
XS Rating Curve= 0 ,0
Exp/Cntr=0.3,0.1

Chan Stop Cuts=-1
Use User Specified Reach Order=0
Composite Channel Slope=5

--- TENMLRUN.g02 (geometry) ---

Geom Title=USGS 10m DEM_copy
Program Version=4.10

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
River Reach=TENMLRUN        ,Main
Reach XY= 30
     1585815.641       390478.03     1585786.558      389175.416
     1585849.448      389086.353     1585727.414       388531.49
     1585904.704      388157.265     1585902.126      387928.207
     1585892.937      387733.762     1585788.524      387647.463
     1585781.869      387490.649     1585707.969      387463.435
     1585693.542      387370.855     1585766.112      387307.489
     1585720.417      387164.295     1585386.997      387226.461
      1585205.89      387342.474     1584829.705      387314.556
     1584614.476      387411.355     1584181.411      387116.099
      1583433.68      386942.795     1582839.687      387126.182
     1582535.835      387305.113     1581952.697      387322.156
     1581553.592      387117.541     1580669.078      386867.207
     1580333.114      386692.876     1580315.102      386488.867
     1579859.316      386193.529     1579907.455      386071.649
     1579836.276      385844.298     1579586.084        385595.3

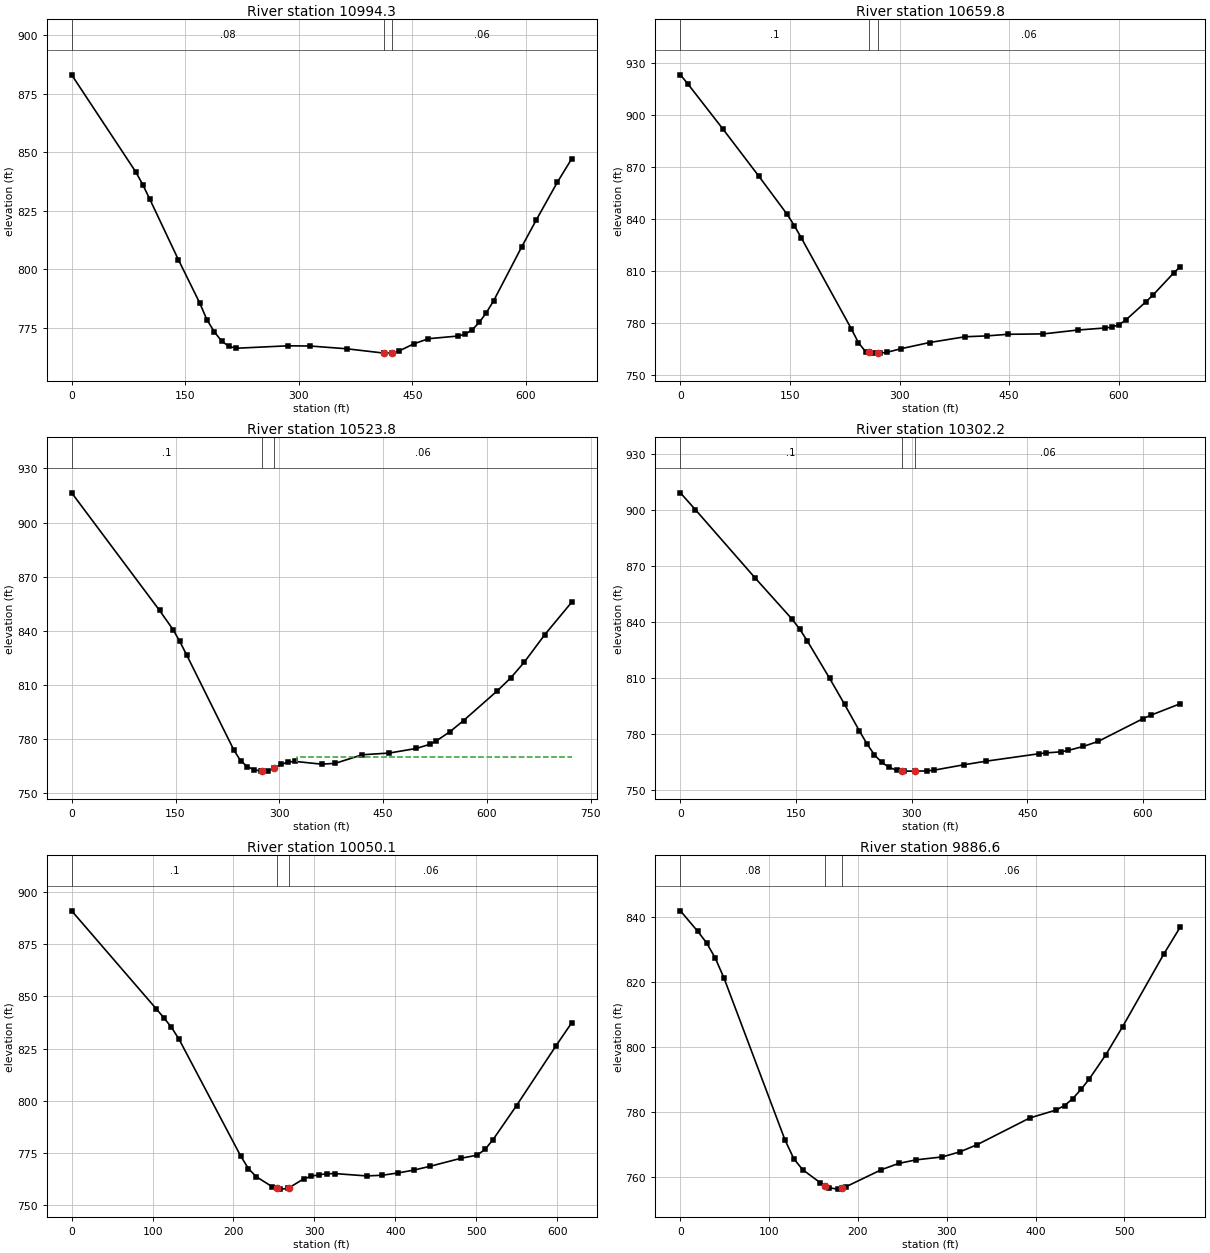
Type RM Length L Ch R = 1 ,10994.3 ,339.4,334.4,328.5
XS GIS Cut Line= 4
     1586206.974      390369.866     1586055.933      390465.352
     1585724.306      390461.095     1585591.523      390531.324
#Sta/Elev= 30
       0  883.12    84.6  841.69      94  836.18   103.4  829.88   141.1  804.08
   169.3  785.59   178.7   778.5   188.4  773.38   198.2  769.35     208   767.1
   217.7  766.34     286  767.38   315.3  767.28     364  766.09   412.2764.2682
   412.8  764.25   423.5764.4058   432.3  765.14   451.8  768.18   471.3  770.41
   510.4  771.55   519.7  772.32   529.1   774.2   538.5  777.38   547.9  781.56
   557.3  786.51   594.8  809.79   613.6  821.01   641.8  837.34   660.6  847.26
#Mann= 3 , 0 , 0
       0     .08       0   412.2    .045       0   423.5     .06       0
Bank Sta=412.2,423.5
XS Rating Curve= 0 ,0
Exp/Cntr=0.3,0.1

Type RM Length L Ch R = 1 ,10659.8 ,131.5,136,139.9
XS GIS Cut Line= 3
     1586081.281      390072.416     1585597.163      390185.057
     1585554.891      390367.609
#Sta/Elev= 30
       0  923.42     9.8   918.4    58.5  891.93   107.2  864.92   146.2  842.71
   155.9  836.27   165.7  828.98   233.9  776.62   243.6  768.58   253.4   763.4
   258.1762.9957   263.1  762.56     270762.5169   272.9   762.5   282.6  762.96
   302.1  765.07   341.1  768.64   389.8  771.98   419.1  772.45   448.3  773.39
     497  773.62   543.9  775.85   581.4  777.05   590.7  777.54   600.1  778.86
   609.5  781.59   637.6  792.33     647  796.14   675.1   808.8   684.4  812.59
#Mann= 3 , 0 , 0
       0      .1       0   258.1    .045       0     270     .06       0
Bank Sta=258.1,270
XS Rating Curve= 0 ,0
Exp/Cntr=0.3,0.1

Type RM Length L Ch R = 1 ,10523.8 ,220.9,221.6,222.1
XS GIS Cut Line= 2
     1586070.316      389991.064     1585348.706        390021.6
#Sta/Elev= 30
       0  916.49   126.9  851.32   146.4  840.69   156.2  834.08   165.9  826.76
   234.2  773.95     244  767.95   253.8  764.68   263.5  763.01   273.1  762.19
  275.47762.2307     283  762.36   292.1763.7997   302.6  765.91   312.3  767.19
   322.1  767.59   361.1  766.05   380.6   766.5   419.7  771.26   458.7  772.21
   497.8  774.76   517.3  777.05     527  779.01   546.6   784.1   566.1  790.23
   614.9  806.74   634.4  813.96   653.9  822.65   683.2  837.75   722.3  855.85
#Mann= 3 , 0 , 0
       0      .1       0  275.47    .045       0   292.1     .06       0
#XS Ineff= 2 , 0
       0                     325       0     770
Permanent Ineff=
       F       F
Bank Sta=275.47,292.1
XS Rating Curve= 0 ,0
Exp/Cntr=0.3,0.1

Type RM Length L Ch R = 1 ,10302.2 ,251.2,252.1,251.8
XS GIS Cut Line= 3
     1586072.469      389782.322     1585530.361      389788.046
     1585468.563      389874.813
#Sta/Elev= 30
       0  909.27    19.4  900.29    96.8  863.78   145.2  841.52   154.9  836.27
   164.6  830.03   193.6  809.99     213  796.05   232.3   781.8     242  774.94
   251.7  769.06   261.4  764.92   271.1  762.29   280.8  760.72   287.2 760.442
   290.4   760.3   304.8 760.305   319.5  760.41   329.2  760.83   367.9  763.71
   396.9  765.64   464.7  769.58   474.4  770.06   493.7  770.62   503.4  771.42
   522.8  773.53   542.1  776.23   600.2  788.39   609.9  790.16   648.7  796.42
#Mann= 3 , 0 , 0
       0      .1       0   287.2    .045       0   304.8     .06       0
Bank Sta=287.2,304.8
XS Rating Curve= 0 ,0
Exp/Cntr=0.3,0.1

Type RM Length L Ch R = 1 ,10050.1 ,163.6,163.4,163.3
XS GIS Cut Line= 3
     1586052.482      389548.019     1585844.149      389535.433
      1585434.86      389534.808
#Sta/Elev= 30
       0  890.92   104.4  844.11   113.8  839.83   123.3  835.23   132.8  829.43
   208.7   773.8   218.5  767.59   228.2  763.75   247.7  759.01   253.8  758.26
   257.4  757.82   267.2  758.14   268.8   758.5   286.7  762.71   296.4  763.99
   306.2  764.76   315.9  765.16   325.6  765.25   364.6  764.13   384.1  764.47
   403.6  765.57   423.1  766.94   442.6  768.71   481.6  772.62   501.1  774.06
   510.8  776.79   520.6   781.4   549.8  797.77   598.5  826.32     618  837.37
#Mann= 3 , 0 , 0
       0      .1       0   253.8    .045       0   268.8     .06       0
Bank Sta=253.8,268.8
XS Rating Curve= 0 ,0
Exp/Cntr=0.3,0.1

Type RM Length L Ch R = 1 ,9886.6  ,197.5,198.8,196.9
XS GIS Cut Line= 3
     1585975.224      389371.634     1585542.496       389373.61
     1585444.409      389287.603
#Sta/Elev= 30
       0  841.77    19.7  835.43    29.5  831.94    39.3  827.26    49.2  821.08
     118  771.32   127.8  765.65   137.7  762.31   157.4  758.34     163757.4412
   167.2  756.77     177  756.34   182.5756.7794   186.9  757.13   226.2  762.28
   245.9  764.23   265.5  765.33     295  766.23   314.7  767.77   334.4     770
   393.4  778.17   422.9   780.6   432.7  781.98     442  784.14   451.4  787.01
   460.7  790.21   479.3  797.64     498  806.16   544.6  828.55   563.2  836.87
#Mann= 3 , 0 , 0
       0     .08       0     163    .045       0   182.5     .06       0
Bank Sta=163,182.5
XS Rating Curve= 0 ,0
Exp/Cntr=0.3,0.1