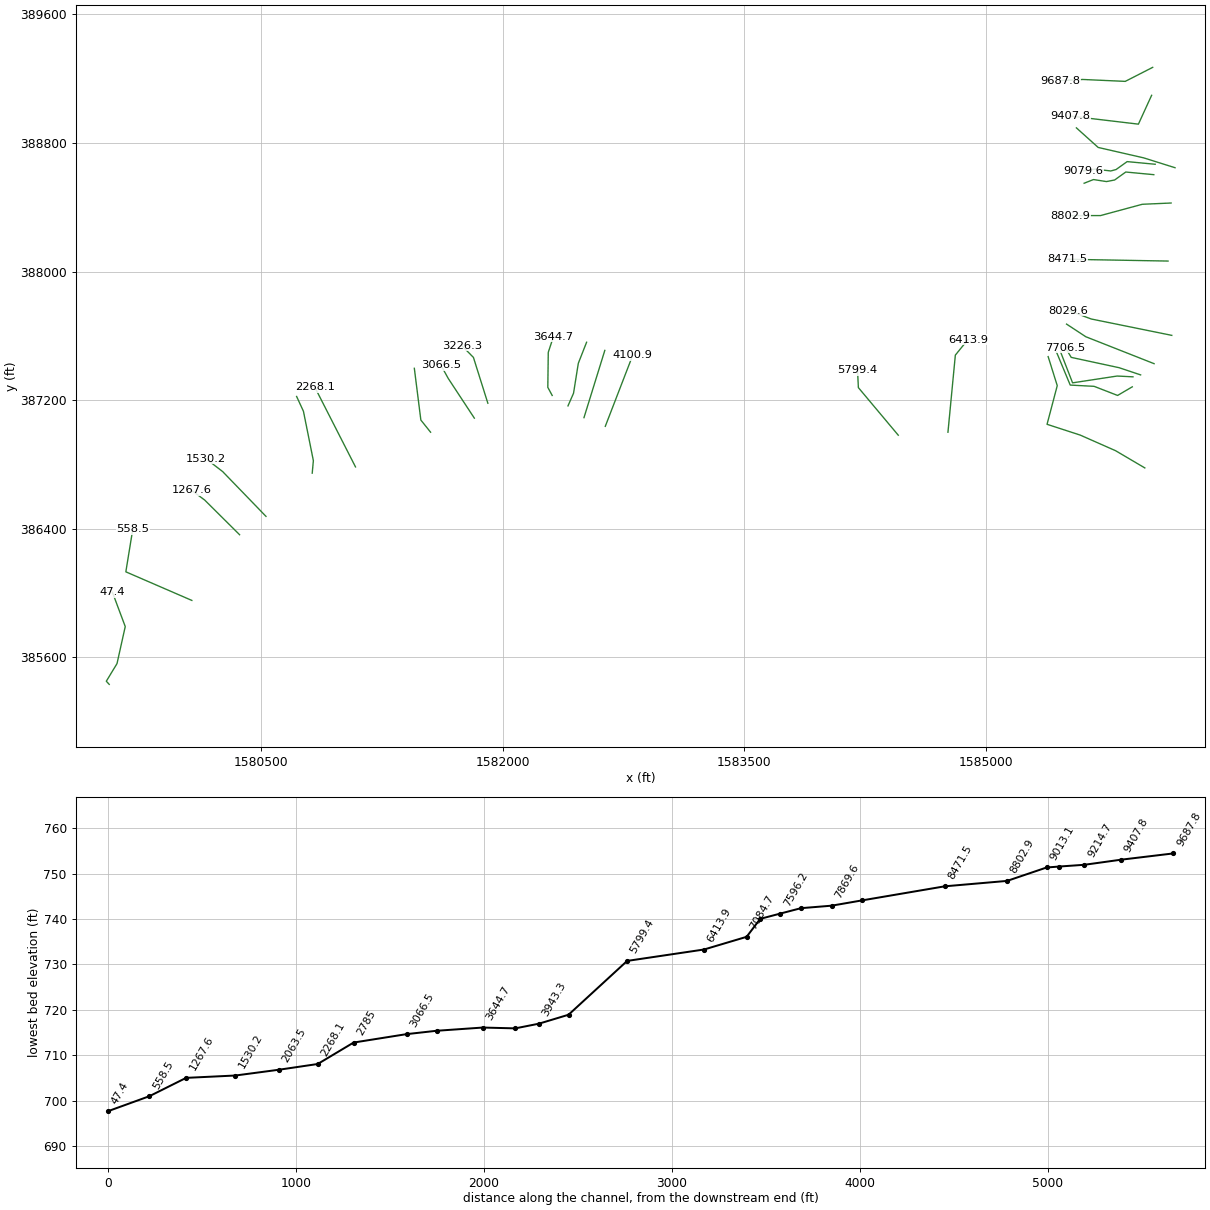
HEC-RAS study TENMLRUN.prj: TENMLRUN

--- TENMLRUN.g02 (geometry) --- (continued)

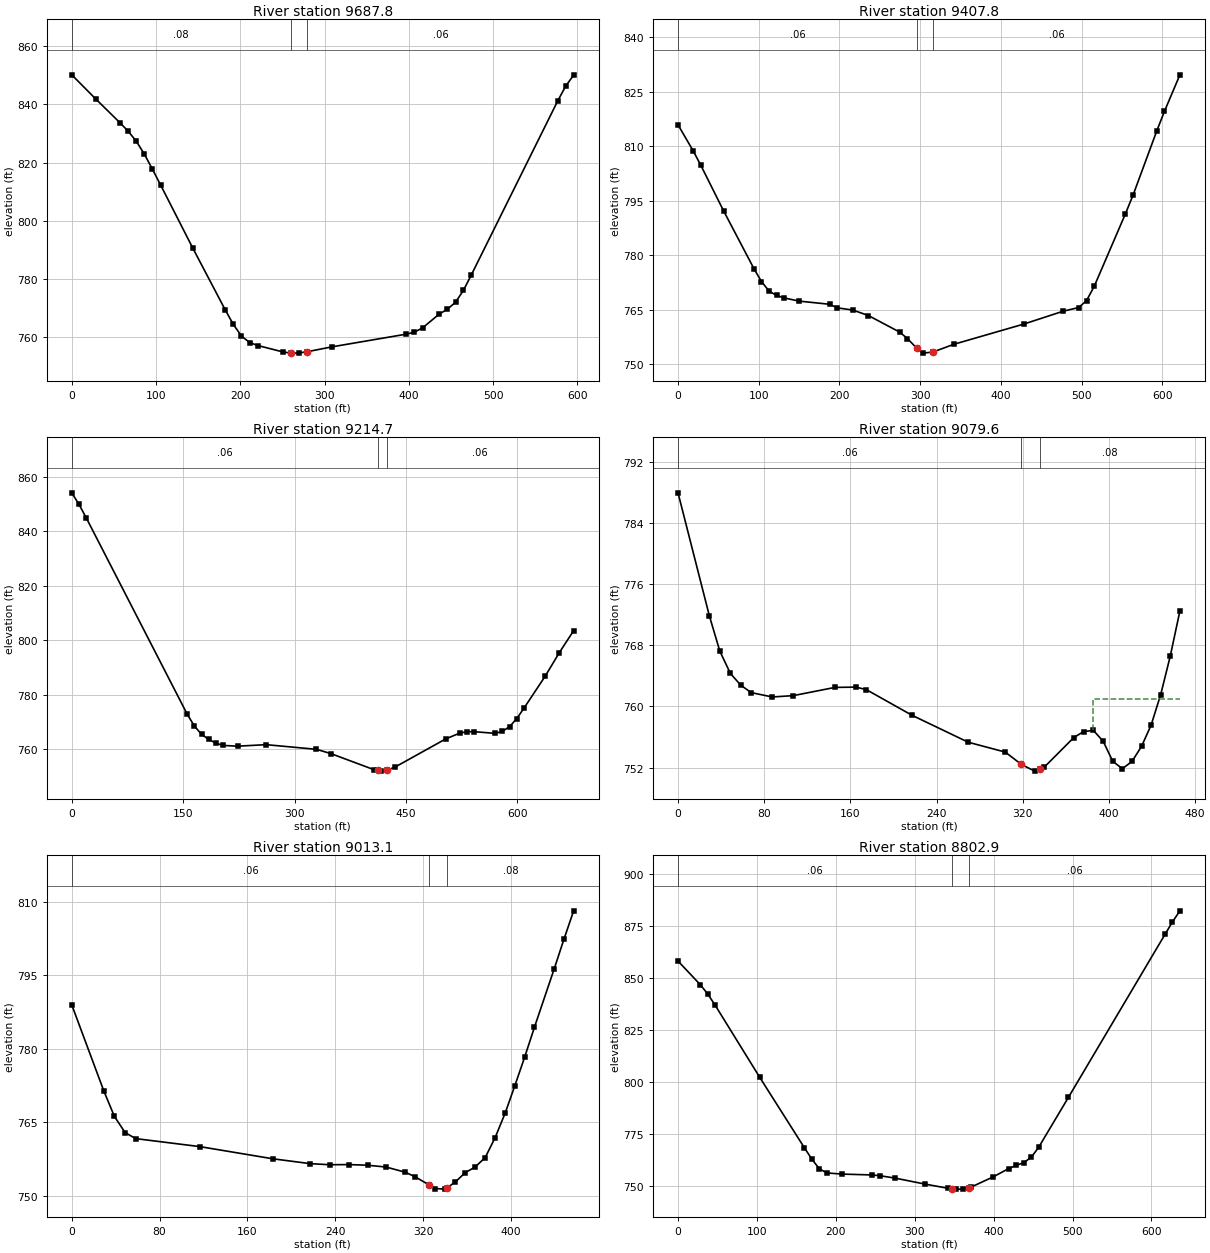
Type RM Length L Ch R = 1 ,9687.8  ,282.6,280,276.4
XS GIS Cut Line= 4
     1586036.534      389270.433     1585866.015      389183.193
     1585602.419       389195.08     1585462.369      389188.401
#Sta/Elev= 30
       0  850.18    28.7   841.8    57.5  833.61      67  830.76    76.6  827.31
    86.2  822.88    95.8  817.66   105.4   812.3   143.6  790.58     182  769.39
   191.5  764.42   201.3  760.33   211.1  758.07   220.9  757.04   250.2  754.87
     260  754.43   269.7  754.48   279.6 754.926   308.8  756.59   396.8  760.95
   406.5  761.64   416.3  763.11   435.9  767.83   445.6  769.51   455.4  771.91
   464.8  776.03   474.1  781.29   576.9  841.32   586.3  846.36   595.6  850.08
#Mann= 3 , 0 , 0
       0     .08       0     260    .045       0   279.6     .06       0
Bank Sta=260,279.6
XS Rating Curve= 0 ,0
Exp/Cntr=0.3,0.1

Type RM Length L Ch R = 1 ,9407.8  ,195,193.2,190.5
XS GIS Cut Line= 3
     1586029.724      389096.573     1585947.743      388917.102
     1585526.173      388967.244
#Sta/Elev= 30
       0  815.87    18.8  808.69    28.2  804.75    56.4  792.22      94  776.31
   103.4  772.73   112.8  770.12   122.1   768.9   131.5  768.22   150.3  767.35
   187.9  766.48   197.3   765.5   216.6  764.89   235.9  763.38   274.5  758.84
   284.2  757.06     296 754.344   303.4  753.04   315.7 753.332     342  755.49
   428.9  761.07   477.1  764.57   496.4  765.58   506.1  767.48   515.7  771.44
   554.3  791.37     564  796.65   592.9  814.04   602.6  819.54   621.8  829.62
#Mann= 3 , 0 , 0
       0     .06       0     296    .045       0   315.7     .06       0
Bank Sta=296,315.7
XS Rating Curve= 0 ,0
Exp/Cntr=0.3,0.1

Type RM Length L Ch R = 1 ,9214.7  ,130.1,135.1,136
XS GIS Cut Line= 4
     1586175.005      388646.054     1585980.573      388707.297
     1585697.913      388772.178     1585562.737      388893.884
#Sta/Elev= 30
       0  854.17     9.7  849.93    19.4  845.03   155.3  772.93     165  768.53
   174.7  765.47   184.4  763.58   194.1   762.2   203.8  761.37   223.2   761.1
   261.8  761.65   329.5  759.94   348.8  758.38   406.9  752.47   411.9  752.19
   416.5  751.93   424.4 752.217   435.9  753.51   503.4  763.74   522.6  765.92
   532.2   766.4   541.7  766.42   570.4   765.8     580  766.58   589.6  768.27
   599.2  771.23   608.7  774.96   637.5  786.81   656.6   795.5   675.8  803.53
#Mann= 3 , 0 , 0
       0     .06       0   411.9    .045       0   424.4     .06       0
Bank Sta=411.9,424.4
XS Rating Curve= 0 ,0
Exp/Cntr=0.3,0.1

Type RM Length L Ch R = 1 ,9079.6  ,69.3,66.5,66.6
XS GIS Cut Line= 6
     1586051.835      388667.553      1585877.79      388684.046
     1585808.779      388634.567     1585776.227      388625.886
     1585677.269      388637.171     1585606.817      388626.295
#Sta/Elev= 30
       0  787.94    29.1  771.85    38.8  767.24    48.6  764.32    58.3  762.77
      68  761.81    87.4  761.24   106.8  761.41   145.7  762.49   165.1  762.53
   174.8   762.2   217.3  758.84   269.4  755.32   303.8  754.03   318.8 752.411
   331.1  751.54   336.3  751.85   340.2  752.09   367.4  755.93   376.5  756.71
   385.6  756.87   394.7  755.44   403.6  752.82   412.5  751.86   421.4   752.8
   430.3  754.78   439.2  757.57   448.1  761.56     457  766.61   465.9  772.49
#Mann= 3 , 0 , 0
       0     .06       0   318.8    .045       0   336.3     .08       0
#XS Ineff= 2 , 0
       0                  385.62       0     761
Permanent Ineff=
       F       F
Bank Sta=318.8,336.3
XS Rating Curve= 0 ,0
Exp/Cntr=0.3,0.1

Type RM Length L Ch R = 1 ,9013.1  ,200.9,210.2,219.3
XS GIS Cut Line= 6
     1586043.374      388602.774     1585869.329      388619.267
     1585800.319      388569.788     1585749.538      388559.806
     1585668.808      388572.392     1585610.723      388549.472
#Sta/Elev= 30
       0  788.95    29.1  771.43    38.8  766.19    48.6  762.87    58.3  761.64
   116.6  760.01   183.2  757.52   217.3  756.53   234.8  756.31   252.2  756.34
   269.4  756.21   286.2  755.84   303.8  754.78     313  753.82   325.5 752.175
   331.1  751.45   340.2  751.33     342  751.62   349.3  752.79   358.3  754.68
   367.4  755.85   376.5  757.76   385.6  761.84   394.7  766.83   403.6  772.48
   412.5  778.28   421.4  784.38   439.3  796.23   448.2   802.3   457.1  808.14
#Mann= 3 , 0 , 0
       0     .06       0   325.5    .045       0     342     .08       0
Bank Sta=325.5,342
XS Rating Curve= 0 ,0
Exp/Cntr=0.3,0.1

Type RM Length L Ch R = 1 ,8802.9  ,336.2,331.5,324.1
XS GIS Cut Line= 4
     1586150.582      388426.437     1585971.718      388418.558
     1585712.332      388348.229     1585524.063      388348.095
#Sta/Elev= 30
       0  858.25    28.3  846.84    37.7  842.36    47.1  836.96   103.6  802.21
   160.2  768.29   169.6  762.83     179  758.23   188.6  756.18   207.8  755.63
   246.2   755.2   255.8  754.85     275   753.7   313.4  750.78   342.2  748.79
   347.6748.5586   351.8  748.38   361.4  748.38   369.3749.1108     371  749.27
   399.8  754.35     419  758.25   428.6  759.82   438.2  761.15   447.8  763.75
   457.2   768.6   494.9  792.63   617.2  871.07   626.6  877.05   636.1  882.44
#Mann= 3 , 0 , 0
       0     .06       0   347.6    .045       0   369.3     .06       0
Bank Sta=347.6,369.3
XS Rating Curve= 0 ,0
Exp/Cntr=0.3,0.1

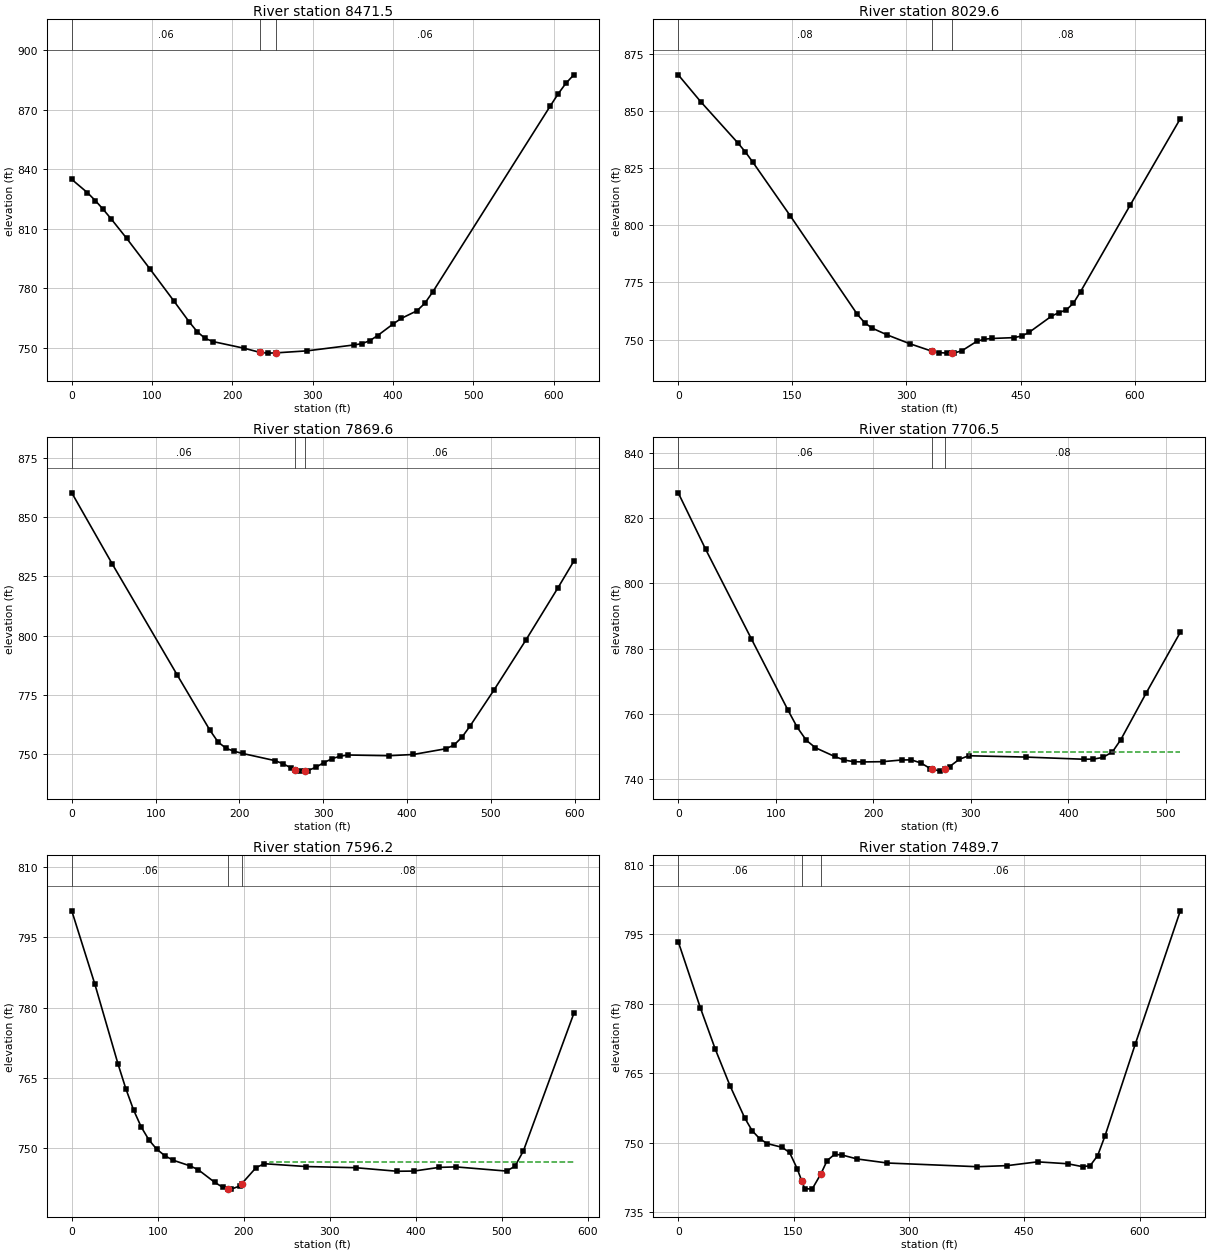
Type RM Length L Ch R = 1 ,8471.5  ,444.3,441.9,437.1
XS GIS Cut Line= 2
     1586131.769       388065.33     1585506.767      388076.539
#Sta/Elev= 30
       0  834.83    19.5  828.14    29.3  824.16    39.1  819.74    48.8  815.03
    68.4  805.06    97.7  789.46     127  773.56   146.5   762.8   156.3  757.94
     166  754.65   175.8  753.02   214.9  749.62     234 747.599   244.2  747.19
   254.8 747.334     293  748.34   351.6  751.33   361.4  751.98   371.2  753.51
   380.9  756.08   400.5  762.02   410.2  764.69   429.8  768.56   439.5  772.31
   449.3  777.98   595.8   871.9   605.6  878.01   615.3  883.38   625.1  887.59
#Mann= 3 , 0 , 0
       0     .06       0     234    .045       0   254.8     .06       0
Bank Sta=234,254.8
XS Rating Curve= 0 ,0
Exp/Cntr=0.3,0.1

Type RM Length L Ch R = 1 ,8029.6  ,165.3,160,153.2
XS GIS Cut Line= 3
     1586155.006      387603.068     1585655.028      387704.849
     1585514.706      387757.424
#Sta/Elev= 30
       0  865.75    29.4  854.06    78.5  835.94    88.3  832.02    98.1  827.55
   147.2  804.15   235.5  761.01   245.3  757.28   255.1  754.98   274.7  752.05
   304.2  748.22   333.1744.9705   343.4  744.31   353.2  744.08   359.6  744.13
     363  744.16   372.9  745.11   392.5  749.23   402.3  750.16   412.1  750.48
   441.6  750.86   451.4  751.55   461.2  753.14   490.6  760.22   500.4  761.78
   510.2  762.96   519.6  765.94     529     771   594.5  808.96   660.1  846.58
#Mann= 3 , 0 , 0
       0     .08       0   333.1    .045       0   359.6     .08       0
Bank Sta=333.1,359.6
XS Rating Curve= 0 ,0
Exp/Cntr=0.3,0.1

Type RM Length L Ch R = 1 ,7869.6  ,150,163.1,168.3
XS GIS Cut Line= 3
     1586045.121      387426.897     1585621.034      387594.536
     1585501.696      387673.145
#Sta/Elev= 30
       0   860.2    48.5   830.1   126.1  783.25   164.9   760.1   174.6  755.16
   184.4  752.47     194  751.28   203.8  750.37   242.6  747.34   252.3  745.99
     262   744.2   266.7743.5824   271.7  742.93   278.5  743.06   281.4  743.12
   291.1  744.55   300.8  746.52   310.5  748.17   320.2  749.25   329.9  749.72
   378.4  749.42   407.5  749.95   446.3  752.37     456  753.92   465.6   757.3
   475.1  761.93   503.6  777.08   541.8  798.23   579.9  820.15   598.9  831.43
#Mann= 3 , 0 , 0
       0     .06       0   266.7    .045       0   278.5     .06       0
Bank Sta=266.7,278.5
XS Rating Curve= 0 ,0
Exp/Cntr=0.3,0.1

Type RM Length L Ch R = 1 ,7706.5  ,105.8,110.3,116.3
XS GIS Cut Line= 4
      1585961.41      387357.088     1585827.982       387401.79
     1585530.552      387466.106     1585494.743      387525.838
#Sta/Elev= 30
       0  827.79    28.1  810.46      75  782.96   112.6  761.04     122  755.82
   131.3  751.84   140.7  749.55   160.4  746.87   170.2  745.78     180  745.27
   189.8   745.2   209.4  745.28   229.1   745.8   238.9  745.84   248.7  744.89
   258.5  743.15     260 743.031   268.3  742.38   273.5  743.11   278.1  743.75
     288  745.99   297.8   747.1   356.7  746.69   415.6  746.03   425.4  746.06
   435.2  746.58     445  748.24   453.7  752.04   479.8   766.4   514.7     785
#Mann= 3 , 0 , 0
       0     .06       0     260    .045       0   273.5     .08       0
#XS Ineff= 2 , 0
       0                  298.42       0  748.28
Permanent Ineff=
       F       F
Bank Sta=260,273.5
XS Rating Curve= 0 ,0
Exp/Cntr=0.3,0.1

Type RM Length L Ch R = 1 ,7596.2  ,113.9,106.5,93.7
XS GIS Cut Line= 4
     1585914.004      387345.111     1585815.392      387349.975
     1585539.004      387307.611     1585464.698      387499.277
#Sta/Elev= 30
       0  800.68    26.9  784.97    53.8  767.93    62.8   762.7    71.8  758.14
    80.8  754.46    89.8  751.69    98.7  749.74   108.4  748.31     118  747.36
   137.3  746.18   146.9  745.36   166.2  742.65   175.9  741.54   182.2  741.31
   185.5  741.19   195.2  741.85   197.7 742.349   214.4   745.8   224.1  746.62
   272.3  746.02   330.1  745.77   378.4  745.01   397.9  745.05   427.3  745.84
   446.9  745.94   505.6  745.05   515.4  746.07   525.2  749.35   583.9  778.76
#Mann= 3 , 0 , 0
       0     .06       0   182.2    .045       0   197.7     .08       0
#XS Ineff= 2 , 0
       0                     230       0     747
Permanent Ineff=
       F       F
Bank Sta=182.2,197.7
XS Rating Curve= 0 ,0
Exp/Cntr=0.3,0.1

Type RM Length L Ch R = 1 ,7489.7  ,72.2,72.2,203.4
XS GIS Cut Line= 5
     1585909.595      387282.868     1585818.454      387229.234
     1585672.825      387285.893      1585524.42      387293.722
     1585439.004      387499.277
#Sta/Elev= 30
       0  793.45    28.8  779.16    48.1  770.28    67.3  762.37    86.5  755.39
    96.1  752.65   105.8  750.94   115.5  749.87     135  749.06   144.8  747.94
   154.6  744.48   160.9   741.7   164.4  740.15   174.1  740.03   185.4743.2719
   193.6  746.18   203.4  747.55   213.2  747.39   232.7  746.54   271.8  745.67
   389.1  744.87   428.2  745.11   467.3  745.92   506.4  745.51   525.9  744.88
   535.7  745.08   545.5  747.27   555.2  751.59   594.3  771.28     653  800.11
#Mann= 3 , 0 , 0
       0     .06       0   160.9    .045       0   185.4     .06       0
Bank Sta=160.9,185.4
XS Rating Curve= 0 ,0
Exp/Cntr=0.3,0.1

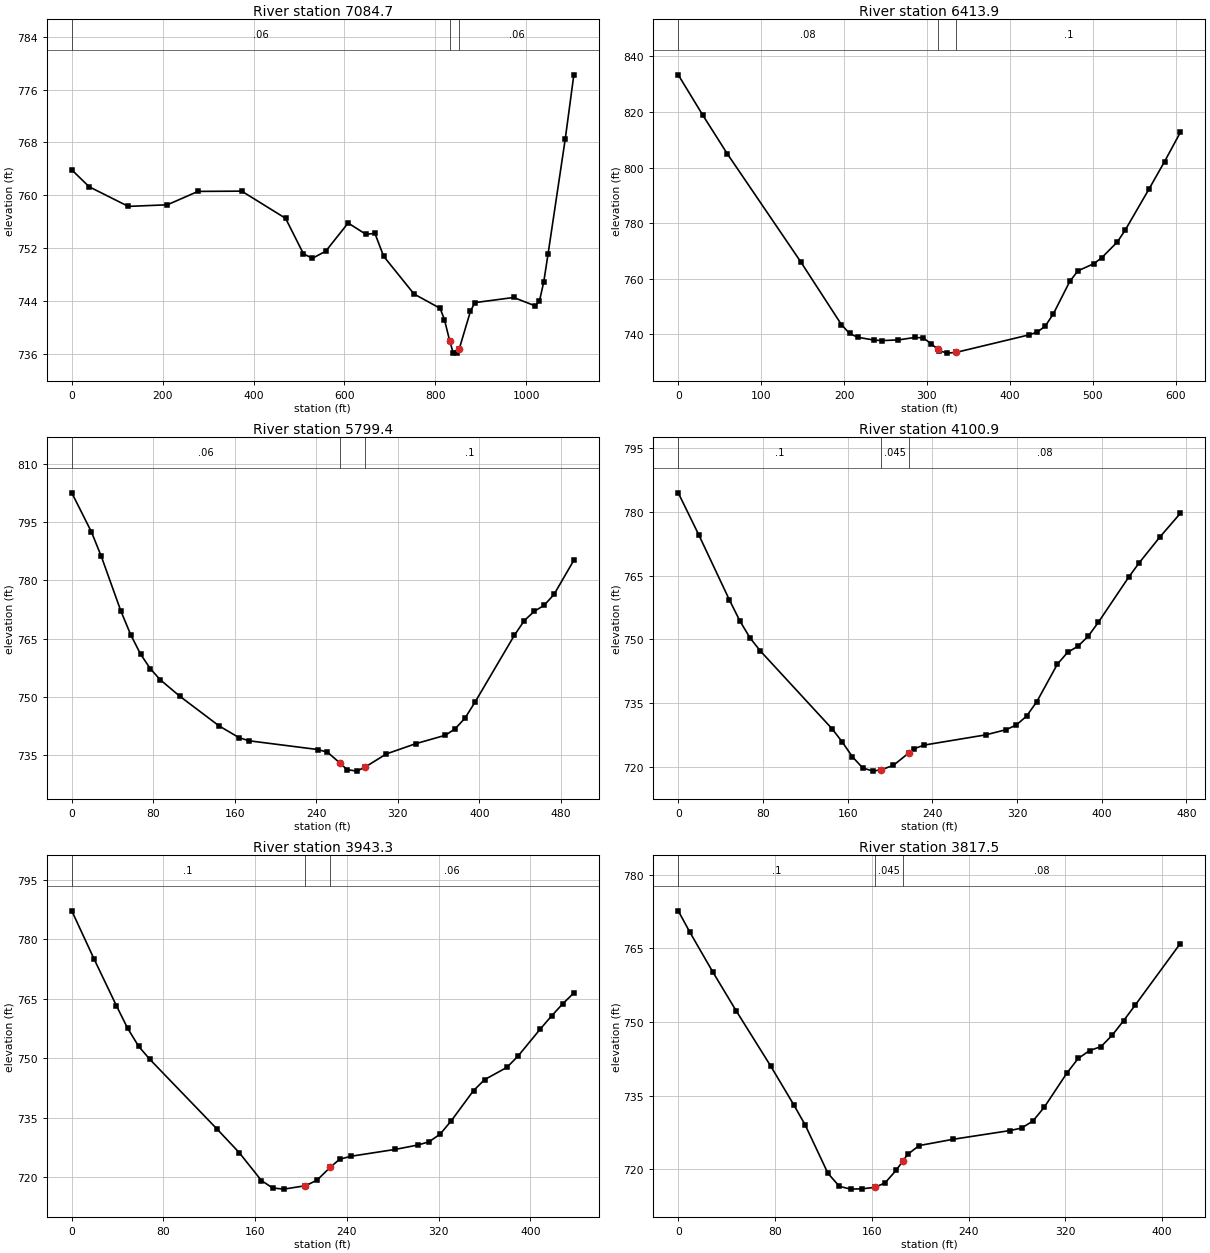
Type RM Length L Ch R = 1 ,7084.7  ,227.6,226.4,224.1
XS GIS Cut Line= 6
     1585987.365      386778.442     1585806.115      386885.386
     1585586.141      386982.726     1585380.539      387049.709
     1585443.832       387290.19     1585387.365      387470.803
#Sta/Elev= 30
       0  763.84    38.3  761.28   124.4  758.31   210.4  758.55   277.8  760.58
     374  760.62   470.6   756.5     510  751.12   529.6  750.44   559.1  751.53
   608.3  755.79   647.6  754.07   667.2  754.23   686.4  750.76   753.3  745.04
   810.7  742.87   820.3  741.15   831.7 737.973   839.4  736.16     849  736.08
     853 736.751   877.6  742.44   887.2  743.73   972.7  744.51    1020  743.24
  1029.4  743.97  1038.9  746.88  1048.4  751.13  1086.2  768.53  1105.1  778.24
#Mann= 3 , 0 , 0
       0     .06       0   831.7    .045       0     853     .06       0
Bank Sta=831.7,853
XS Rating Curve= 0 ,0
Exp/Cntr=0.3,0.1

Type RM Length L Ch R = 1 ,6413.9  ,396.6,409.1,420
XS GIS Cut Line= 3
     1584765.263      387000.255      1584811.16      387480.159
     1584888.957      387576.111
#Sta/Elev= 30
       0  833.35    29.5  818.91      59  805.04   147.6  766.19   196.8  743.57
   206.6  740.37   216.4  738.99   236.1  737.99     246   737.8   265.6  738.04
   285.3  738.92   295.2  738.78     305  736.73     313 734.624   314.8  734.15
   324.7  733.29   335.5  733.58   423.1  739.85   432.9  740.84   442.7  742.99
   452.6  747.49   472.3  759.08   482.1  762.88   501.1  765.42   510.6  767.52
   529.6  773.25   539.1   777.5   567.6  792.16   586.6  802.16   605.6  812.64
#Mann= 3 , 0 , 0
       0     .08       0     313    .045       0   335.5      .1       0
Bank Sta=313,335.5
XS Rating Curve= 0 ,0
Exp/Cntr=0.3,0.1

Type RM Length L Ch R = 1 ,5799.4  ,323.1,311.7,299.9
XS GIS Cut Line= 3
     1584456.809      386981.914     1584209.148      387277.909
     1584204.031      387384.692
#Sta/Elev= 30
       0   802.6    19.3  792.51      29  786.19    48.2  772.09    57.9  765.95
    67.5  760.98    77.2  757.17    86.8  754.37   106.1  750.09   144.7  742.43
     164  739.45   173.7  738.62   241.2  736.36   250.9  735.68   262.9 732.947
   270.2  731.17   279.8  730.78   287.9 731.818   308.8  735.22   337.7  737.87
   366.6  740.03   376.3   741.7   385.9  744.43   395.7  748.54   434.5  765.86
   444.2  769.64     454  772.03   463.7  773.58   473.4   776.4   492.8   785.2
#Mann= 3 , 0 , 0
       0     .06       0   262.9    .045       0   287.9      .1       0
Bank Sta=262.9,287.9
XS Rating Curve= 0 ,0
Exp/Cntr=0.3,0.1

Type RM Length L Ch R = 1 ,4100.9  ,155.8,157.7,159
XS GIS Cut Line= 2
     1582637.872      387037.066     1582808.385       387479.54
#Sta/Elev= 30
       0  784.53    19.4  774.63    48.4  759.25    58.1  754.39    67.7  750.38
    77.4   747.3   145.2  728.95   154.8  725.85   164.5  722.32   174.2   719.7
   183.9  718.94   191.7  719.26   203.2   720.3   218.2 723.316   222.6  724.21
   232.3  725.08   290.3  727.48   309.7  728.71   319.4  729.82     329  731.91
   338.7  735.32   358.1  744.15   367.7  746.92   377.4  748.36   387.1  750.69
   396.8  754.02   425.8  764.78   435.5  768.08   454.8  774.08   474.2  779.69
#Mann= 3 , 0 , 0
       0      .1       0   191.7    .045       0   218.2     .08       0
Bank Sta=191.7,218.2
XS Rating Curve= 0 ,0
Exp/Cntr=0.3,0.1

Type RM Length L Ch R = 1 ,3943.3  ,121.2,125.8,128.7
XS GIS Cut Line= 2
     1582505.595      387091.063     1582634.935      387509.466
#Sta/Elev= 30
       0  787.16    19.5  774.98    38.9  763.25    48.7  757.55    58.4  752.96
    68.1   749.7   126.5  732.18     146  726.19   165.4  719.14   175.2  717.26
   184.9  716.97     203 717.791   204.4  717.87   214.1  719.29   225.5   722.5
   233.6   724.5   243.3  725.25   282.2  726.99   301.7  728.09   311.4  728.88
   321.2  730.81   330.9  734.17   350.4  741.82   360.1  744.59   379.6  747.69
   389.3  750.55   408.7  757.37   418.5  760.66   428.2  763.71   437.9  766.44
#Mann= 3 , 0 , 0
       0      .1       0     203    .045       0   225.5     .06       0
Bank Sta=203,225.5
XS Rating Curve= 0 ,0
Exp/Cntr=0.3,0.1

Type RM Length L Ch R = 1 ,3817.5  ,170.1,172.8,176
XS GIS Cut Line= 4
     1582406.304      387164.247     1582440.812      387243.136
     1582470.421      387429.162     1582521.756      387560.081
#Sta/Elev= 30
       0  772.64     9.6  768.29    28.7  760.13    47.8  752.31    76.5  740.99
    95.5  733.13   104.9  729.04   123.8  719.15   133.2  716.51   142.6  715.94
     152  716.01   162.3 716.291   170.9  717.19   180.3  719.82   185.5  721.59
   189.7  723.02   199.1  724.81   227.4   726.1   274.5  727.88   283.8  728.38
   293.2   729.8   302.6  732.62   321.4  739.61   330.7  742.57   340.1  744.17
   349.5  744.97   358.8   747.3   368.2  750.25   377.6  753.36   415.1  765.98
#Mann= 3 , 0 , 0
       0      .1       0   162.3    .045       0   185.5     .08       0
Bank Sta=162.3,185.5
XS Rating Curve= 0 ,0
Exp/Cntr=0.3,0.1

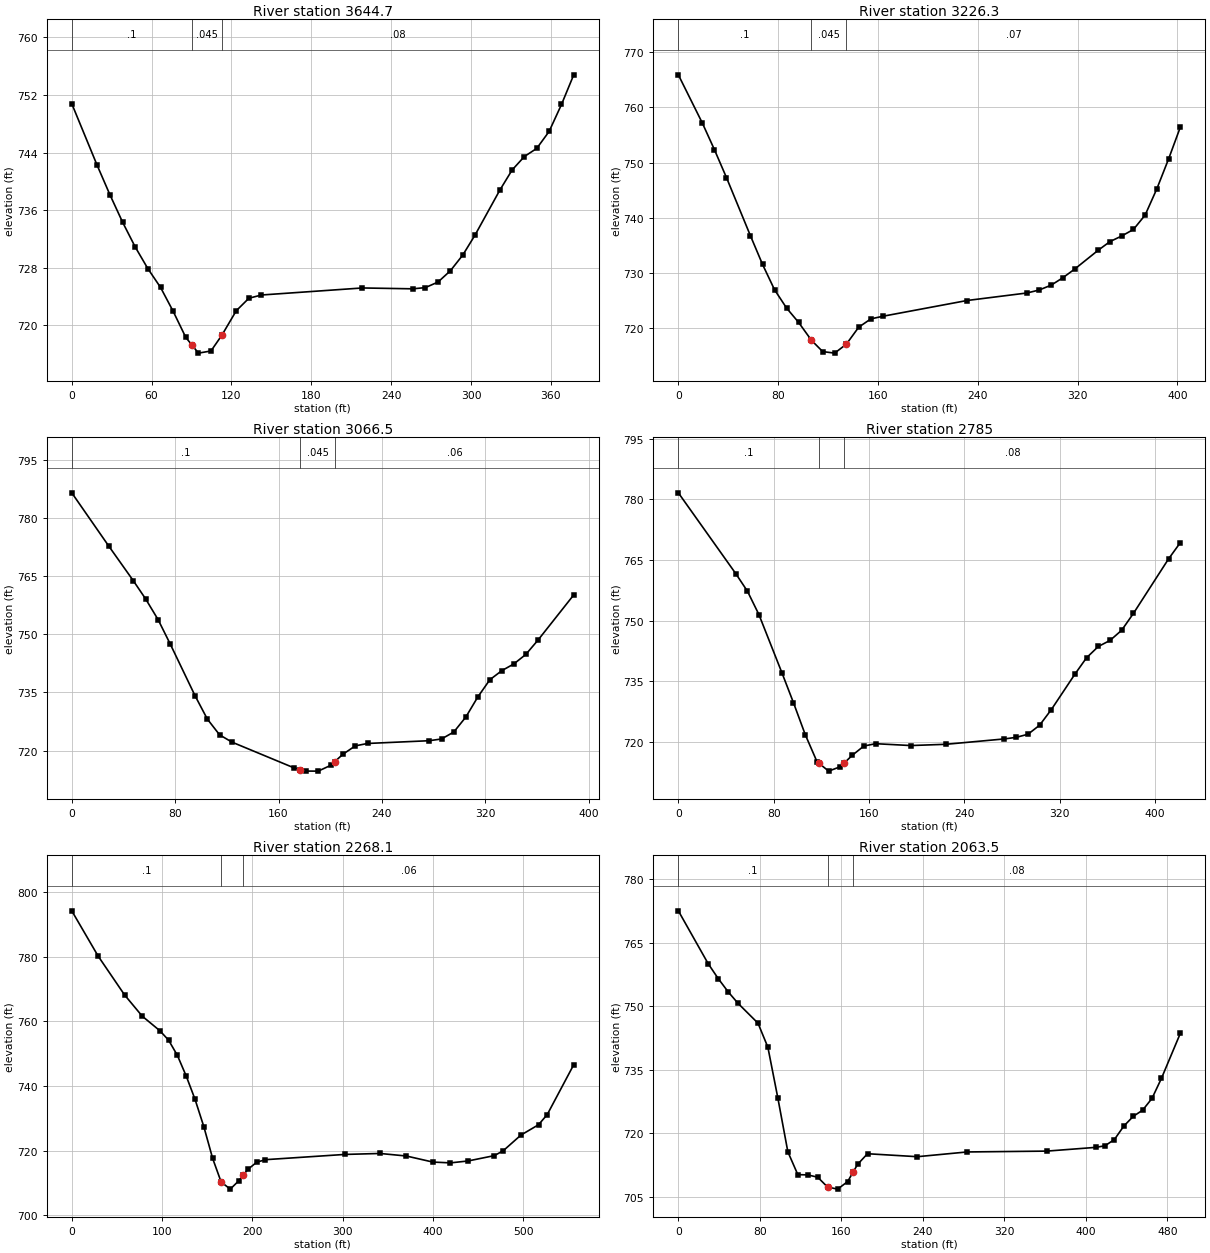
Type RM Length L Ch R = 1 ,3644.7  ,246.5,245.8,244.2
XS GIS Cut Line= 4
     1582308.198      387229.136     1582281.123      387279.582
     1582283.889      387497.522     1582315.837      387594.414
#Sta/Elev= 30
       0   750.8    19.1  742.22    28.6  738.17    38.2  734.32    47.7  730.87
    57.2  727.86    66.7  725.26    76.2  721.93    85.7   718.3      90 717.316
    95.2  716.12   104.6  716.42   112.8 718.612   123.6  722.01   133.1  723.75
   142.5   724.2   218.4  725.18   256.3  725.06   265.7  725.23   275.2     726
   284.5  727.57   293.8  729.75     303  732.52   321.6  738.76   330.9  741.58
   340.1  743.45   349.4  744.58   358.7  746.94     368  750.69   377.2  754.81
#Mann= 3 , 0 , 0
       0      .1       0      90    .045       0   112.8     .08       0
Bank Sta=90,112.8
XS Rating Curve= 0 ,0
Exp/Cntr=0.3,0.1

Type RM Length L Ch R = 1 ,3226.3  ,153.5,159.8,166
XS GIS Cut Line= 3
      1581908.88      387180.692      1581819.26      387465.839
     1581746.654      387539.588
#Sta/Elev= 30
       0  765.92    19.3  757.14    28.9  752.35    38.6  747.26    57.8  736.71
    67.5  731.51    77.1  726.92    86.8  723.58    96.4  720.99   106.7 717.743
   115.7  715.69   125.3  715.41   134.7 717.038   144.6  720.12   154.3  721.62
   163.9   722.1   231.4  724.96   279.6  726.33   289.3  726.87   298.9  727.75
   308.3   729.1   317.7  730.66   336.5  734.07   345.9  735.64   355.4  736.67
   364.8  737.85   374.2  740.47   383.6  745.24     393  750.65   402.4  756.42
#Mann= 3 , 0 , 0
       0      .1       0   106.7    .045       0   134.7     .07       0
Bank Sta=106.7,134.7
XS Rating Curve= 0 ,0
Exp/Cntr=0.3,0.1

Type RM Length L Ch R = 1 ,3066.5  ,292.3,281.5,270.8
XS GIS Cut Line= 3
     1581824.865      387088.164     1581662.682      387335.361
      1581617.92      387416.636
#Sta/Elev= 30
       0  786.59    28.6  772.84    47.7  763.84    57.2  759.15    66.8  753.82
    76.3  747.44    95.4  734.15   104.9  728.12   114.4  724.04     124  722.16
   171.7  715.55   176.8 715.083   181.2  714.68   190.7  714.67   200.3  716.16
   203.6 717.157   209.8  719.03   219.4   721.2   228.9  721.82   276.6  722.53
   286.1  722.98   295.6  724.78   304.9  728.64   314.2  733.85   323.5  738.29
   332.8  740.65     342  742.36   351.3  744.82   360.6  748.47   388.4  760.21
#Mann= 3 , 0 , 0
       0      .1       0   176.8    .045       0   203.6     .06       0
Bank Sta=176.8,203.6
XS Rating Curve= 0 ,0
Exp/Cntr=0.3,0.1

Type RM Length L Ch R = 1 ,2785    ,184.9,191,196.8
XS GIS Cut Line= 3
     1581553.253      387000.622     1581492.888      387076.097
     1581452.382      387397.987
#Sta/Elev= 30
       0  781.59    48.3  761.57      58  757.26    67.6   751.5      87  737.04
    96.6  729.71   106.5  721.81   116.3  715.16   117.8   714.8   126.1  712.82
     136  713.93   139.3 714.866   145.8  716.71   155.6  719.02   165.5   719.6
     195  719.14   224.4  719.45   273.6  720.78   283.4  721.17   293.3  721.93
   303.1  724.18   312.9  728.03   332.6  736.75   342.4  740.82   352.3  743.62
   362.1  745.11   371.9  747.63   381.8  751.81   411.2  765.25   421.1  769.28
#Mann= 3 , 0 , 0
       0      .1       0   117.8    .045       0   139.3     .08       0
Bank Sta=117.8,139.3
XS Rating Curve= 0 ,0
Exp/Cntr=0.3,0.1

Type RM Length L Ch R = 1 ,2268.1  ,210.6,204.6,198.3
XS GIS Cut Line= 2
     1581087.126      386784.568     1580834.923       387279.81
#Sta/Elev= 30
       0  794.17    29.2  780.17    58.5  768.15      78   761.6    97.5   757.1
   107.2  754.18     117  749.43   126.8  743.02   136.5  735.86   146.2  727.44
     156  717.59   165.4   710.3   175.5   708.1   185.2  710.76   189.9 712.415
     195  714.21   204.8  716.43   214.5  717.21   302.3  718.83   341.3  719.13
   370.5  718.34   399.8  716.47   419.3  716.22   438.8  716.81     468  718.47
   477.8  719.99   497.3  724.81   516.8  728.01   526.5  731.18   555.8  746.58
#Mann= 3 , 0 , 0
       0      .1       0   165.4    .045       0   189.9     .06       0
Bank Sta=165.4,189.9
XS Rating Curve= 0 ,0
Exp/Cntr=0.3,0.1

Type RM Length L Ch R = 1 ,2063.5  ,223.7,232.8,241.6
XS GIS Cut Line= 4
     1580818.457      386745.845     1580825.517      386823.675
     1580764.013      387130.523     1580721.582      387222.928
#Sta/Elev= 30
       0  772.58    29.3  760.09    39.1  756.59    48.8  753.48    58.6  750.73
    78.2  746.04    87.9  740.36    97.7  728.35   107.5  715.67   117.3  710.27
     127  710.21   136.8  709.67   146.5  707.34   156.4  706.85   166.2  708.63
   171.5 710.837     176  712.71   185.7  715.21   234.6  714.51   283.5  715.63
   361.8  715.83   409.6  716.71   418.8  717.08   428.1  718.57   437.3  721.73
   446.6  724.04   455.8   725.5     465  728.28   474.3  733.03   492.8  743.64
#Mann= 3 , 0 , 0
       0      .1       0   146.5    .045       0   171.5     .08       0
Bank Sta=146.5,171.5
XS Rating Curve= 0 ,0
Exp/Cntr=0.3,0.1

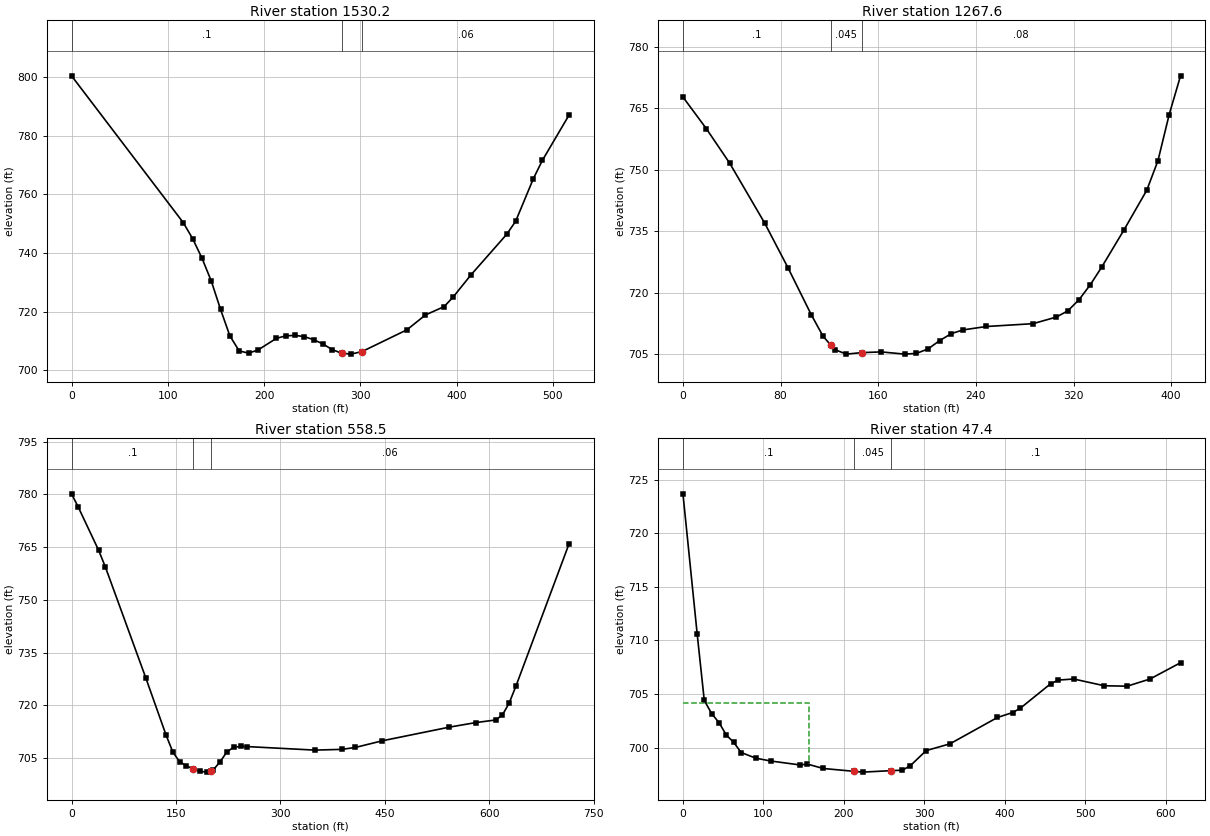
Type RM Length L Ch R = 1 ,1530.2  ,260.9,262.6,262.1
XS GIS Cut Line= 3
     1580531.434      386476.902     1580262.588      386755.402
     1580159.709        386834.8
#Sta/Elev= 30
       0  800.36   116.1  750.35   125.8  744.92   135.5  738.26   145.2  730.46
   154.8  720.81   164.5  711.79   174.2  706.65   183.9  705.92   193.6  706.95
   212.9  710.96   222.6  711.79   232.3  711.97   241.9  711.52   251.6  710.49
   261.3  709.02     271  707.07   280.6   705.9   290.3  705.57   301.8 706.439
   348.4  713.84   367.7  718.91   387.1  721.75   396.4  724.98   414.9  732.52
   452.1  746.37   461.4  750.81   479.9  765.38   489.2  771.57     517  787.04
#Mann= 3 , 0 , 0
       0      .1       0   280.6    .045       0   301.8     .06       0
Bank Sta=280.6,301.8
XS Rating Curve= 0 ,0
Exp/Cntr=0.3,0.1

Type RM Length L Ch R = 1 ,1267.6  ,194.9,195.2,194.4
XS GIS Cut Line= 3
     1580367.544      386362.777     1580150.634      386578.673
     1580068.954      386639.184
#Sta/Elev= 30
       0  767.77    19.1  760.08    38.3  751.63      67     737    86.1   726.1
   105.2  714.63   114.8  709.42   120.9 707.333   124.3  706.17   133.9  705.05
   146.4 705.419   162.6  705.59   181.7  705.05   191.3  705.23   200.8  706.31
   210.4  708.37     220  710.06   229.5  710.96   248.7  711.79   286.9  712.48
     306   714.1   315.3   715.6   324.5  718.31   333.8  721.99     343  726.23
   361.5  735.42     380  745.01   389.2  752.24   398.4   763.5   407.7  772.94
#Mann= 3 , 0 , 0
       0      .1       0   120.9    .045       0   146.4     .08       0
Bank Sta=120.9,146.4
XS Rating Curve= 0 ,0
Exp/Cntr=0.3,0.1

Type RM Length L Ch R = 1 ,558.5   ,226.3,220.9,214.8
XS GIS Cut Line= 3
     1580071.063      385954.025     1579661.317        386131.9
     1579704.337      386396.684
#Sta/Elev= 30
       0  780.15     9.7  776.35    38.8  764.15    48.6  759.35   106.8  727.75
     136  711.44   145.7  706.66   155.4  703.96   165.1  702.81   174.8  701.93
   184.5  701.27   194.2  701.02   200.3 701.462   203.9  701.72   213.6     704
   223.3  706.81   233.1   708.1   242.8  708.33   252.5  708.28   349.6  707.28
   388.4  707.49   407.8  708.04   446.7  709.94   542.5   713.8   580.8  715.11
   609.6  715.85   619.1   717.3   628.7  720.64   638.3  725.39   714.9  766.01
#Mann= 3 , 0 , 0
       0      .1       0   174.8    .045       0   200.3     .06       0
Bank Sta=174.8,200.3
XS Rating Curve= 0 ,0
Exp/Cntr=0.3,0.1

Type RM Length L Ch R = 1 ,47.4    ,15.6,47.4,90
XS GIS Cut Line= 5
      1579558.06      385431.827     1579540.084      385451.312
     1579606.491      385560.906     1579657.653      385791.316
     1579578.135      386004.537
#Sta/Elev= 30
       0  723.68    17.7  710.59    26.5   704.4    35.7  703.17    44.8  702.33
      54  701.16    63.1  700.49    72.3  699.54    90.6  699.01   108.9  698.75
   145.5  698.38   154.6  698.46   174.3  698.05   212.3 697.786   223.5  697.71
   258.6 697.849   272.7  697.89   282.5  698.31   302.2  699.72   331.7  700.35
   390.7  702.81   409.6  703.27   419.1  703.67     457  705.97   466.5   706.3
   485.5   706.4   523.4  705.77   551.9  705.73   580.3   706.4   618.2  707.92
#Mann= 3 , 0 , 0
       0      .1       0   212.3    .045       0   258.6      .1       0
#XS Ineff= 2 , 0
          156.16  704.15
Permanent Ineff=
       F       F
Bank Sta=212.3,258.6
XS Rating Curve= 0 ,0
Exp/Cntr=0.3,0.1